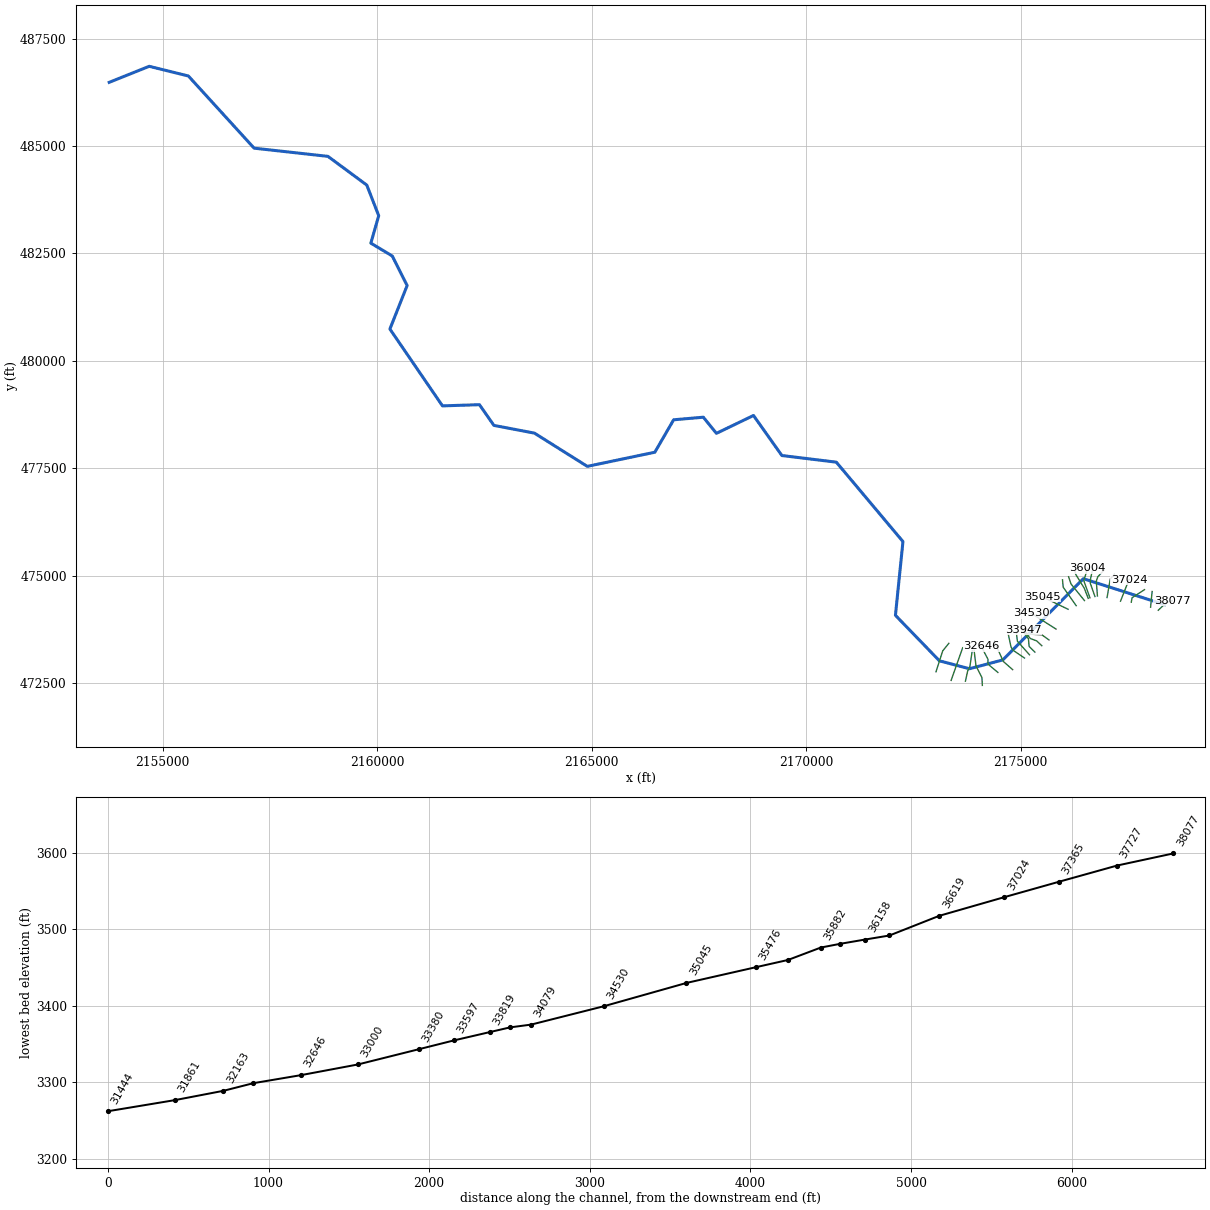
--- MFWILLIAMSRV.prj (project) ---

Proj Title=MFWILLIAMSRV
Current Plan=p01
Default Exp/Contr=0.3,0.1
English Units
Geom File=g01
Flow File=f01
Plan File=p01
Y Axis Title=Elevation
X Axis Title(PF)=Main Channel Distance
X Axis Title(XS)=Station
BEGIN DESCRIPTION:
----------MODEL BY WOOD PLC 2021----------
Stream Name: Middle Fork Williams River
Flood Zone: Enhanced Approximate
Pocahontas County, WV
HEC-RAS Version: RAS 6.1
Vertical Datum: NAVD88
Projection: NAD 1983 StatePlane West Virginia S FIPS 4702 (US Feet)
Terrain: 1-meter LIDAR (FEMA Region III 3DEP collected 2016-2018)
Land Use: 2019 NLCD
Hydrologic Method:
WV SIR2010-5033 regression equations
END DESCRIPTION:
DSS Export Rating Curves= 0
DSS Export Rating Curve Sorted= 0
DSS Export Volume Flow Curves= 0
DXF OffsetX= 0
DXF OffsetY= 0
DXF ScaleX= 1
DXF ScaleY= 10

--- MFWILLIAMSRV.p01 (plan) ---

Plan Title=Floodplain
Program Version=6.10
Short Identifier=Floodplain
Geom File=g01
Flow File=f01
Subcritical Flow
K Sum by GR= 0
Std Step Tol= 0.01
Critical Tol= 0.01
Num of Std Step Trials= 20
Max Error Tol= 0.3
Flow Tol Ratio= 0.001
Split Flow NTrial= 30
Split Flow Tol= 0.02
Split Flow Ratio= 0.02
Log Output Level= 0
Friction Slope Method= 1
Unsteady Friction Slope Method= 2
Unsteady Bridges Friction Slope Method= 1
Parabolic Critical Depth
Global Vel Dist= 0 , 0 , 0
Global Log Level= 0
CheckData=True
Encroach Param=-1 ,0,0, 0
Computation Interval=1MIN
Output Interval=1HOUR
Instantaneous Interval=1HOUR
Mapping Interval=1HOUR
Computation Time Step Use Courant=        0
Computation Time Step Use Time Series=    0
Computation Time Step Count To Double=0
Computation Time Step Max Doubling=0
Computation Time Step Max Halving=0
Computation Time Step Residence Courant=0
Run HTab= 0
Run UNet= 0
Run Sediment= 0
Run PostProcess= 0
Run WQNet= 0
Run RASMapper=-1
UNET Theta= 1
UNET Theta Warmup= 1
UNET ZTol= 0.02
UNET ZSATol= 0.02
UNET MxIter= 20
UNET Max Iter WO Improvement= 0
UNET MaxInSteps= 0
UNET DtIC= 0
UNET DtMin= 0
UNET MaxCRTS= 20
UNET WFStab= 2
UNET SFStab= 1
UNET WFX= 1
UNET SFX= 1
UNET Gravity=32.174
UNET 1D Methodology=Finite Difference
UNET DSS MLevel= 4
UNET Pardiso=0
UNET DZMax Abort= 100
UNET Use Existing IB Tables=-1
UNET Froude Reduction=False
UNET Froude Limit= 0.8
UNET Froude Power= 4
UNET D1 Cores= 0
UNET WindReference=Eulerian
UNET WindDragFormulation=Hsu (1988)
UNET D2 Coriolis=0
UNET D2 Cores= 0
UNET D2 Theta= 1
UNET D2 Theta Warmup= 1
UNET D2 Z Tol= 0.01
UNET D2 Volume Tol= 0.01
UNET D2 Max Iterations= 20
UNET D2 Equation= 0
UNET D2 RampUpFraction=0.1
UNET D2 TimeSlices= 1
UNET D2 Turbulence Formulation=None
UNET D2 Eddy Viscosity=0.3
UNET D2 Transverse Eddy Viscosity=0.1
UNET D2 Smagorinsky Mixing=0.05
UNET D2 BCVolumeCheck=0
UNET D2 Cores=0
UNET D2 SolverType=PARDISO (Direct)
UNET D2 Minimum Iterations= 2147483647
UNET D2 Maximum Iterations= 2147483647
UNET D2 Restart Number= 10
UNET D2 Relaxation Coeff=1.3
UNET D2 SOR Precondition Iterations= 10
UNET D2 ILUT Maximum Fill= 8
UNET D2 ILUT Tolerance=1E-08
UNET D1D2 MaxIter= 0
UNET D1D2 ZTol=0.01
UNET D1D2 QTol=0.1
UNET D1D2 MinQTol=1
Write IC File= 0
Write IC File at Fixed DateTime=0
Write IC File at Sim End=0
Echo Input=False
Echo Parameters=False
Echo Output=False
Write Detailed= 0
HDF Write Warmup=0
HDF Write Time Slices=0
HDF Flush=0
HDF Compression= 1
HDF Chunk Size= 1
HDF Spatial Parts= 1
HDF Use Max Rows=0
HDF Fixed Rows= 1
Calibration Method= 0
Calibration Iterations= 20
Calibration Max Change=0.05
Calibration Tolerance=0.2
Calibration Maximum=1.5
Calibration Minimum=0.5
Calibration Optimization Method= 1
WQ AD Non Conservative
WQ ULTIMATE=-1
WQ Max Comp Step=1HOUR
WQ Output Interval=15MIN
WQ Output Selected Increments= 0
WQ Output face flow=0
WQ Output face velocity=0
WQ Output face area=0
WQ Output face dispersion=0
WQ Output cell volume=0
WQ Output cell surface area=0
WQ Output cell continuity=0
WQ Output cumulative cell continuity=0
WQ Output face conc=0
WQ Output face dconc_dx=0
WQ Output face courant=0
WQ Output face peclet=0
WQ Output face adv mass=0
WQ Output face disp mass=0
WQ Output cell mass=0
WQ Output cell source sink temp=0
WQ Output nsm pathways=0
WQ Output nsm derived pathways=0
WQ Create Restart=0
WQ Fixed Restart=0
WQ System Summary=0
WQ Write To DSS=0
Sorting and Armoring Iterations= 10
XS Update Threshold= 0.02
Bed Roughness Predictor= 0
Hydraulics Update Threshold= 0.02
Energy Slope Method= 1
Volume Change Method= 1
Sediment Retention Method= 0
Sediment TS Multiplier= 1
Warm Up Method= 0
XS Weighting Method= 0
Number of US Weighted Cross Sections= 1
Number of DS Weighted Cross Sections= 1
Upstream XS Weight=0
Main XS Weight=1
Downstream XS Weight=0
Number of DS XS's Weighted with US Boundary= 1
Upstream Boundary Weight= 1
Weight of XSs Associated with US Boundary= 0
Number of US XS's Weighted with DS Boundary= 1
Downstream Boundary Weight= 0.5
Weight of XSs Associated with DS Boundary= 0.5
Percentile Method= 0
Sediment Output Level= 3
Mass or Volume Output= 0
Output Increment Type= 1
Profile and TS Output Increment= 1
Transport Output Increment 1
XS Output Flag= 0
XS Output Increment= 10
Read HDF5 Sediment Hotstart= 0
Sediment Hotstart Type= 0
Write Gradation File= 0
Read Gradation Hotstart= 0
Write HDF5 File= 1
Write Binary Output= 1
Write DSS Sediment File= 0
DSS Sediment Output Type= 1
SV Curve= 0
Specific Gage Flag= 0
Subcell Erosion Methods= 0
Subcell Deposition Methods= 0
Advection Scheme= 1
Matrix Solver= 0
Implicit Weighting Factor= 1
Maximum Outer Loop Convergence Iterations= 5
Convergence Maximum Absolute= 0.001
Convergence RMSE= 0.0001
Grain Fractions Max Abs Error= 0.001
Max Subgrid Regions= 1
Max Subgrid Length Scale= 3.402823E+38
Initial Layer Thickness= 3.402823E+38
Min Layer Thickness= 3.402823E+38
Max Layer Thickness= 3.402823E+38
Number of Layers= 5

--- MFWILLIAMSRV.f01 (steady flow) ---

Flow Title=Flow
Program Version=6.10
Number of Profiles= 6
Profile Names=01pct,10pct,04pct,02pct,0_2pct,01plus
River Rch & RM=MFWILLIAMSRV,Main            ,38077
     812     435     574     689    1130    1200
River Rch & RM=MFWILLIAMSRV,Main            ,32349
    1200     650     853    1020    1650    1770
River Rch & RM=MFWILLIAMSRV,Main            ,30973
    1340     731     957    1140    1840    1980
River Rch & RM=MFWILLIAMSRV,Main            ,28508
    1510     829    1080    1290    2070    2230
River Rch & RM=MFWILLIAMSRV,Main            ,23700
    1680     925    1210    1430    2300    2480
River Rch & RM=MFWILLIAMSRV,Main            ,18676
    1970    1090    1420    1680    2690    2910
River Rch & RM=MFWILLIAMSRV,Main            ,13286
    2310    1290    1670    1980    3140    3410
River Rch & RM=MFWILLIAMSRV,Main            ,7775
    2980    1680    2160    2560    4040    4410
River Rch & RM=MFWILLIAMSRV,Main            ,6066
    3320    1880    2420    2850    4480    4910
Boundary for River Rch & Prof#=MFWILLIAMSRV,Main            , 1
Up Type= 0
Dn Type= 3
Dn Slope=0.02499
Boundary for River Rch & Prof#=MFWILLIAMSRV,Main            , 2
Up Type= 0
Dn Type= 3
Dn Slope=0.02499
Boundary for River Rch & Prof#=MFWILLIAMSRV,Main            , 3
Up Type= 0
Dn Type= 3
Dn Slope=0.02499
Boundary for River Rch & Prof#=MFWILLIAMSRV,Main            , 4
Up Type= 0
Dn Type= 3
Dn Slope=0.02499
Boundary for River Rch & Prof#=MFWILLIAMSRV,Main            , 5
Up Type= 0
Dn Type= 3
Dn Slope=0.02499
Boundary for River Rch & Prof#=MFWILLIAMSRV,Main            , 6
Up Type= 0
Dn Type= 3
Dn Slope=0.02499
DSS Import GetInterval= 0
DSS Import GetPeak= 0
DSS Import FillOption= 0

--- MFWILLIAMSRV.g01 (geometry) ---

Geom Title=Geometry
Program Version=6.10

River Reach=MFWILLIAMSRV    ,Main
Reach XY= 30
2178350.03559922 474325.512697222176457.17225897474928.966214731
2174580.70783605473038.366977558 2173802.8492006472832.954588915
2173103.56577723473017.0356553942172077.80667388474076.516476065
2172253.05861998475793.1524784712170699.91408847477641.480146647
2169430.67876606477796.2331179832168769.39235897478728.222723812
2167905.38096364478312.3032800562167599.92127272478688.120441809
2166908.30618614478627.9686592222166470.14597322477872.769710317
2164895.75148422477543.7802108082163662.87698147478317.782271728
2162718.91725522 478497.41281797 2162382.1387293478979.465987727
 2161519.8806113478951.9706358912160294.96606639 480740.62978822
2160696.61782214481752.6841945652160349.90690139482441.152633891
2159850.82555047482739.9299234752160034.50005189483378.660273314
2159755.86758537 484091.77119453 2158851.0335868484759.828770816
2157130.02381278484950.665709522 2155597.3805862 486630.98068303
2154684.84424875486856.2927571942153752.09949217486482.737160358

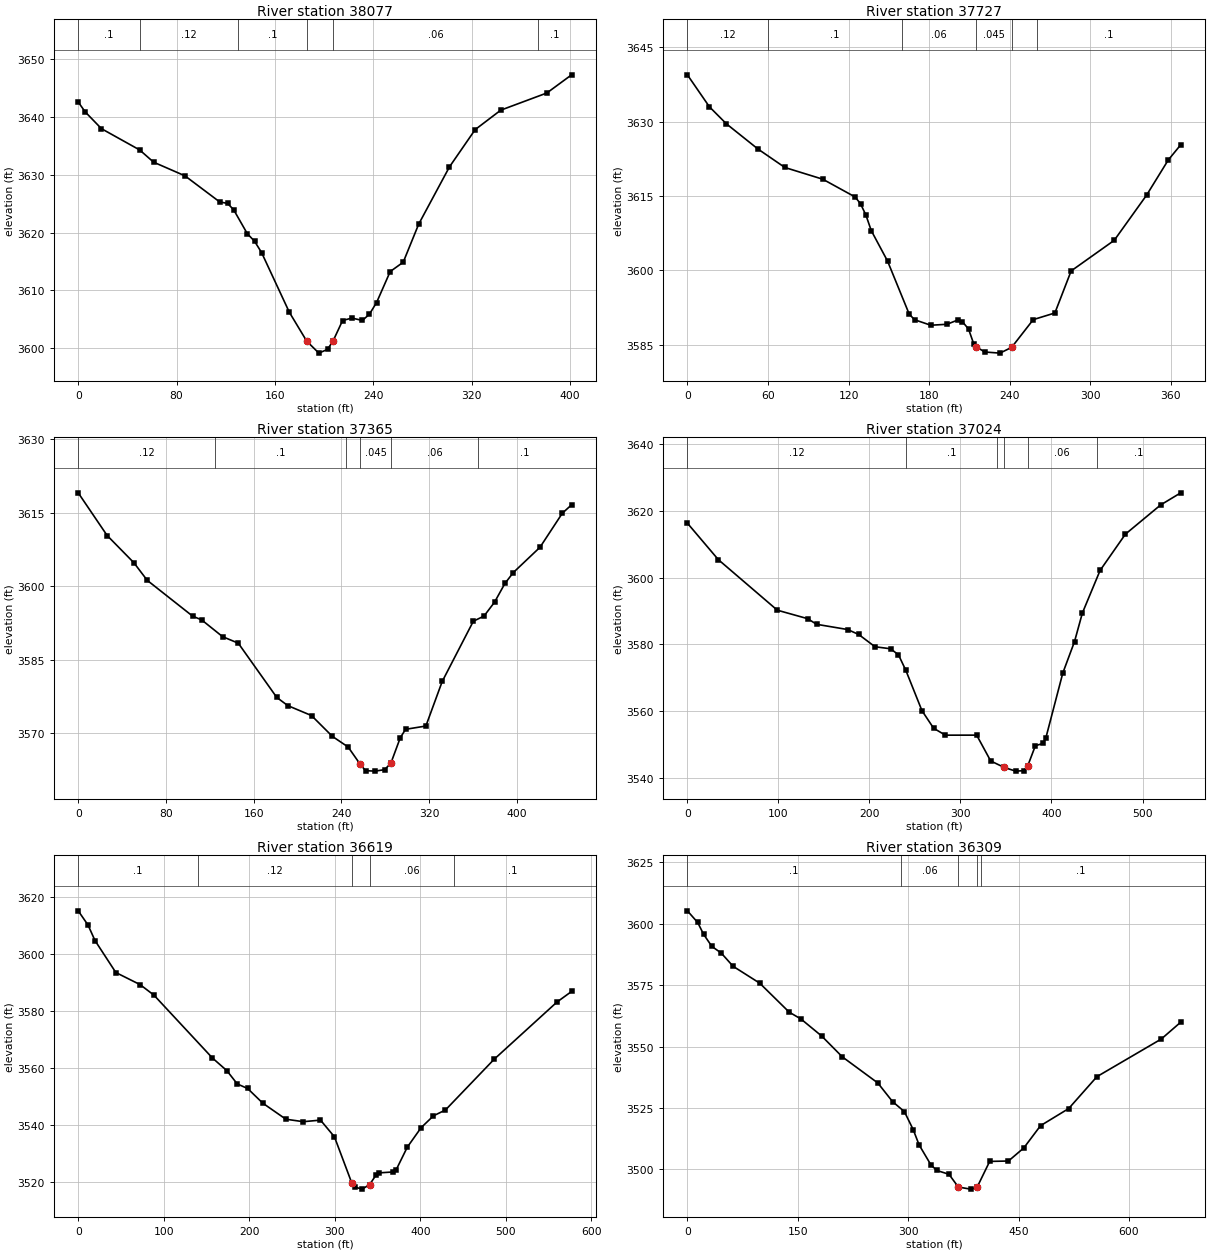
Type RM Length L Ch R = 1 ,38077   ,335.3,350.1,360.1
XS GIS Cut Line= 3
2178204.04657631474194.5938995422178395.35688139474375.783984759
 2178527.3004384474415.052900536
#Sta/Elev= 30
       0 3642.58     5.7 3640.87    18.9 3637.97      50 3634.29    61.3 3632.18
    86.8 3629.82   115.1  3625.3   121.4 3625.06   126.4 3623.96   137.5 3619.82
   143.4 3618.51   149.1 3616.56   171.7 3606.23   185.8 3601.25   195.7 3599.17
   202.8 3599.83   207.4 3601.34     215 3604.81   222.6 3605.23   231.1 3604.82
   236.8  3605.9   242.6  3607.9   253.7 3613.27   264.3 3614.89   276.9 3621.48
   301.9 3631.37   322.8 3637.81   343.6 3641.17   381.1 3644.14   401.2 3647.28
#Mann= 6 ,-1,0
       0      .1       0      50     .12       0     130      .1       0
   185.8    .045       0   207.4     .06       0  373.49      .1       0
Bank Sta=185.8,207.4
XS Rating Curve= 0 ,0
Exp/Cntr(USF)=0,0
Exp/Cntr=0.3,0.1

Type RM Length L Ch R = 1 ,37727   ,374.6,361.7,341.2
XS GIS Cut Line= 2
2178024.74558071474264.8905058112178060.62088649474630.430783537
#Sta/Elev= 30
       0 3639.42    16.4 3632.98      29 3629.56    52.5 3624.48    72.6 3620.75
   100.8 3618.39   124.9 3614.81   128.9 3613.44   132.9 3611.17   136.9 3608.03
     149 3601.91   165.1 3591.24   169.1 3590.08   181.2 3588.97   193.2 3589.16
   201.3 3590.02   204.7  3589.7   209.3 3588.21   213.3 3585.13   214.9 3584.66
   221.3 3583.58   232.7 3583.35   241.4 3584.51   257.5  3590.1   273.6 3591.44
   285.7 3599.91   317.8 3606.08   341.9 3615.19     358 3622.26   367.3 3625.33
#Mann= 6 ,-1,0
       0     .12       0      60      .1       0     160     .06       0
   214.9    .045       0   241.4     .06       0     260      .1       0
Bank Sta=214.9,241.4
XS Rating Curve= 0 ,0
Exp/Cntr(USF)=0,0
Exp/Cntr=0.3,0.1

Type RM Length L Ch R = 1 ,37365   ,327.5,341.2,351.1
XS GIS Cut Line= 3
2177574.84985428474383.182054571 2177593.2723086474485.959957592
2177883.18356335474674.062912178
#Sta/Elev= 30
       0 3619.09    26.4 3610.36    50.8 3604.79      63 3601.19   104.4 3593.87
   112.6 3593.11   131.7 3589.68     146 3588.35   181.1 3577.26   191.2 3575.58
   212.8 3573.55   231.8  3569.3   246.2 3567.12   257.3 3563.56   262.1 3562.28
   270.8 3562.19   279.5 3562.49   285.2 3563.83   293.8 3569.04   298.6 3570.74
   317.1 3571.41     332 3580.52   360.4 3592.84   370.1 3593.89   379.7 3596.72
   389.2 3600.56   396.9  3602.8   421.2 3607.96   441.6 3614.93     450 3616.64
#Mann= 6 ,-1,0
       0     .12       0  124.42      .1       0  244.42     .06       0
   257.3    .045       0   285.2     .06       0  364.42      .1       0
Bank Sta=257.3,285.2
XS Rating Curve= 0 ,0
Exp/Cntr(USF)=0,0
Exp/Cntr=0.3,0.1

Type RM Length L Ch R = 1 ,37024   ,399.4,405,407.3
XS GIS Cut Line= 2
2177323.72271388474405.4829203212177522.49129991 474909.67640684
#Sta/Elev= 30
       0  3616.3      34 3605.37    98.8 3590.23   132.1 3587.69     142    3586
     176 3584.44   188.2 3582.96   206.1 3579.28   223.3 3578.67   231.9 3576.86
     240 3572.21   257.7 3560.14   270.5 3554.88   283.4  3552.8   317.8 3552.81
   333.2 3545.08   347.9 3543.15   360.6 3542.03   369.4 3542.16   373.7 3543.46
   382.3 3549.64   390.9 3550.34   393.9 3552.07   412.4 3571.38   425.3 3580.83
   433.9 3589.36   453.4 3602.14   481.2    3613   519.9 3621.75     542 3625.38
#Mann= 6 ,-1,0
       0     .12       0     240      .1       0     340     .06       0
   347.9    .045       0   373.7     .06       0     450      .1       0
Bank Sta=347.9,373.7
XS Rating Curve= 0 ,0
Exp/Cntr(USF)=0,0
Exp/Cntr=0.3,0.1

Type RM Length L Ch R = 1 ,36619   ,312.8,310.2,306.8
XS GIS Cut Line= 3
2177010.54099053474489.8383690272177084.23080779474923.250846861
2177177.31268222475024.089544165
#Sta/Elev= 30
       0 3615.07    11.5 3610.08    19.6 3604.68      44 3593.47    72.4 3589.23
    88.6 3585.54   156.9 3563.56   173.8 3559.12     186 3554.46   198.1 3552.87
   215.8 3547.74   242.8 3542.12   263.1 3541.25   283.3  3541.8   299.6 3535.96
   319.9 3519.78   323.9 3518.33     332 3517.64   340.7 3519.21   348.3 3522.59
   352.3 3523.34   368.6 3523.66   371.9 3524.47   384.8 3532.33     401 3539.17
   415.4 3543.31   429.4 3545.34   486.2 3563.06   559.8 3583.13   576.9 3586.84
#Mann= 5 ,-1,0
       0      .1       0     140     .12       0   319.9    .045       0
   340.7     .06       0  439.63      .1       0
Bank Sta=319.9,340.7
XS Rating Curve= 0 ,0
Exp/Cntr(USF)=0,0
Exp/Cntr=0.3,0.1

Type RM Length L Ch R = 1 ,36309   ,148.7,150.3,158.1
XS GIS Cut Line= 4
2176785.91192203474527.2558988042176759.33977259474874.627029083
2176796.05642853474975.7847293932176942.37418276475132.379488307
#Sta/Elev= 30
       0  3605.3      14 3600.56      22 3595.76    33.2 3590.83    46.1 3588.07
    62.1 3582.71    98.2 3575.85   138.3 3564.04   154.4 3561.22   182.5 3554.29
   210.5 3545.82   258.7 3535.19   278.7 3527.61   294.8 3523.52   306.8 3516.19
   314.8 3509.97   330.9 3501.81   338.9 3499.54   355.4 3497.99   368.1 3492.79
   384.7 3491.94   393.7 3492.76   410.7 3503.23   436.2 3503.39   457.1 3508.73
   479.8 3517.78   518.1 3524.77   556.4 3537.75   643.9 3553.09   670.3 3559.95
#Mann= 5 ,-1,0
       0      .1       0     290     .06       0   368.1    .045       0
   393.7     .06       0  398.39      .1       0
Bank Sta=368.1,393.7
XS Rating Curve= 0 ,0
Exp/Cntr(USF)=0,0
Exp/Cntr=0.3,0.1

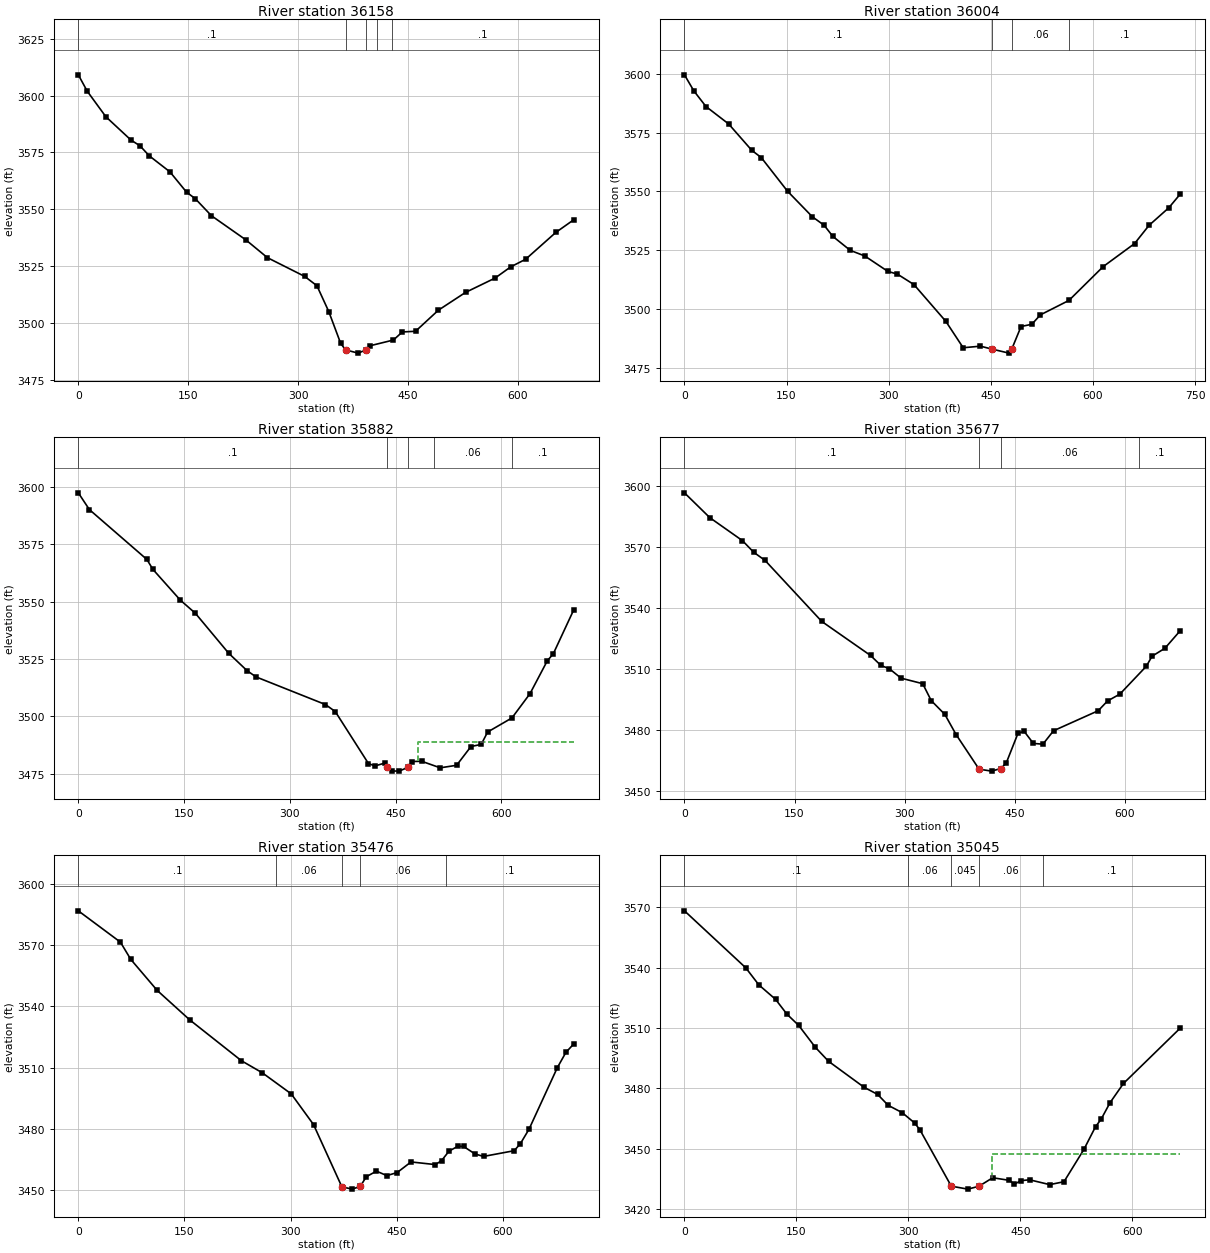
Type RM Length L Ch R = 1 ,36158   ,160,154.7,151.1
XS GIS Cut Line= 4
2176728.17571764474513.6666908212176619.37269897474822.766175679
2176625.55468866474932.805592288  2176679.956198475165.248404901
#Sta/Elev= 30
       0 3609.14    12.2 3601.92    37.6 3590.71    71.8 3580.47    84.3 3577.88
      97 3573.47   125.1 3566.45   147.9 3557.48   159.6 3554.68   181.8 3547.14
   228.5 3536.59   258.2  3528.7     309 3520.47   325.8 3516.35     342 3504.97
   358.2 3491.01   364.9 3488.12   382.2  3486.7   393.1  3488.2   398.2 3489.93
   430.3 3492.47   442.4 3496.02   460.4 3496.31   491.7  3505.6   528.7 3513.41
     569 3519.71   590.4 3524.65   610.8    3528   651.9 3539.78   676.6  3545.4
#Mann= 5 ,-1,0
       0      .1       0   364.9    .045       0   393.1      .1       0
  407.69     .06       0  427.69      .1       0
Bank Sta=364.9,393.1
XS Rating Curve= 0 ,0
Exp/Cntr(USF)=0,0
Exp/Cntr=0.3,0.1

Type RM Length L Ch R = 1 ,36004   ,108.6,122.2,140.8
XS GIS Cut Line= 3
2176611.59047102474484.1421214782176467.32144799474883.647029669
2176558.08161922475172.805998681
#Sta/Elev= 30
       0 3599.55    13.9 3592.68    31.6 3586.07    64.9 3578.65    98.9 3567.42
   112.8 3564.35   151.4 3550.03   187.8 3539.17   205.2 3535.52     218 3530.79
   243.5 3524.86   264.8 3522.48   298.8  3515.9   312.8 3514.75   337.1 3510.29
   383.9 3494.66   409.4 3483.42   434.7 3484.09   451.5 3482.86   476.7 3481.13
     481 3483.03   494.4 3492.46   510.2  3493.4   522.8 3497.41   564.7 3503.55
     615 3517.94   661.1 3527.74   682.4 3535.51   711.4 3542.98   727.8 3548.66
#Mann= 4 ,-1,0
       0      .1       0   451.5    .045       0     481     .06       0
  564.76      .1       0
Bank Sta=451.5,481
XS Rating Curve= 0 ,0
Exp/Cntr(USF)=0,0
Exp/Cntr=0.3,0.1

Type RM Length L Ch R = 1 ,35882   ,202,204.4,206.9
XS GIS Cut Line= 4
2176571.41553885474470.5386078522176478.54837455474707.948555852
 2176279.9531636475029.9922390792176262.71982396475097.489486029
#Sta/Elev= 30
       0 3597.34    15.7 3590.04    97.2 3568.35   105.9 3563.98   144.6 3550.66
   166.1 3544.88   213.3  3527.5   239.2 3519.97     252 3517.21   350.6 3505.16
   364.5 3502.11   411.6 3479.46   420.9 3478.44   434.9 3479.71   438.43478.067
   444.3 3476.26   455.2 3476.18     4683477.899   472.8 3480.37   487.2 3480.46
   513.3 3477.62   536.6 3478.72     557  3486.9   571.5  3487.8   580.6  3493.2
   615.1 3499.34   640.7  3509.9   665.3 3524.24   673.7 3527.23   702.9  3546.5
#Mann= 5 ,-1,0
       0      .1       0   438.4    .045       0     468      .1       0
  504.93     .06       0  614.93      .1       0
#XS Ineff= 2 , 0
                          481.45         3488.66
Permanent Ineff=
       F       F
Bank Sta=438.4,468
XS Rating Curve= 0 ,0
Exp/Cntr(USF)=0,0
Exp/Cntr=0.3,0.1

Type RM Length L Ch R = 1 ,35677   ,201.5,200.7,199.3
XS GIS Cut Line= 3
2176483.36892563474419.7004474242176169.32384901474807.929400406
2176113.68594174474974.843122229
#Sta/Elev= 30
       0  3596.6    34.6  3584.4    79.1 3573.11    94.3 3567.45   109.9  3563.4
   187.1 3533.47   253.6 3516.75   267.8 3511.83   279.2 3510.25   295.2 3505.61
   324.7  3502.9   336.3 3494.59   354.9 3487.81   370.2 3477.91   401.5 3460.94
   418.5 3459.97   431.2 3461.26   438.5 3463.92   454.6 3478.59     463 3479.47
   475.5 3473.57   488.5  3473.2     503 3479.79   563.9 3489.63   576.6 3494.42
   593.4 3497.78   629.5 3511.48   637.2 3516.37   654.8 3520.29   675.3 3528.77
#Mann= 4 ,-1,0
       0      .1       0   401.5    .045       0   431.2     .06       0
  619.35      .1       0
Bank Sta=401.5,431.2
XS Rating Curve= 0 ,0
Exp/Cntr(USF)=0,0
Exp/Cntr=0.3,0.1

Type RM Length L Ch R = 1 ,35476   ,413.9,431.2,438.8
XS GIS Cut Line= 3
2176290.89403826474300.4820759652175987.64376147474731.416679828
2175971.68322059474904.322539402
#Sta/Elev= 30
       0 3586.72    59.5  3571.4    74.2 3562.94   111.5 3547.76   157.6 3533.31
   230.7 3513.31   260.1 3507.43     301 3497.11   332.6 3482.05   372.6 3451.62
     387 3450.47   398.6 3451.77   407.2 3456.55   421.5 3459.28   436.2 3457.09
   450.8 3458.58   470.4 3463.78   504.9 3462.48   513.5  3464.4   524.2 3469.09
   536.7 3471.46   544.8 3471.35   560.8 3467.69   572.9 3466.48   616.3 3469.28
   625.1 3472.77   637.2 3479.78   677.3 3509.97   689.4 3517.42   700.6 3521.61
#Mann= 5 ,-1,0
       0      .1       0     280     .06       0   372.6    .045       0
   398.6     .06       0     520      .1       0
Bank Sta=372.6,398.6
XS Rating Curve= 0 ,0
Exp/Cntr(USF)=0,0
Exp/Cntr=0.3,0.1

Type RM Length L Ch R = 1 ,35045   ,520.6,515.2,512.4
XS GIS Cut Line= 2
2176101.99479719474217.3953096362175504.29552952474506.392757738
#Sta/Elev= 30
       0 3568.34    82.1 3540.02    99.8 3531.47     122 3524.36   137.3 3516.96
   153.1 3511.35   175.3 3500.51   193.1 3493.51   240.8 3480.57   258.8 3477.06
     273 3471.62   291.7    3468   308.6 3462.78   315.7  3459.3   357.5 3431.43
   379.7 3429.96   394.6 3431.39     413 3435.62   435.5 3434.31   441.9 3432.38
   450.8 3434.17   462.4  3434.6   489.4  3432.2   508.5 3433.64   535.2 3449.71
   550.8 3461.02   558.3 3464.75   570.2 3472.93   588.2 3482.51   663.9 3509.89
#Mann= 5 ,-1,0
       0      .1       0     300     .06       0   357.5    .045       0
   394.6     .06       0     480      .1       0
#XS Ineff= 2 , 0
                             412         3447.66
Permanent Ineff=
       F       F
Bank Sta=357.5,394.6
XS Rating Curve= 0 ,0
Exp/Cntr(USF)=0,0
Exp/Cntr=0.3,0.1

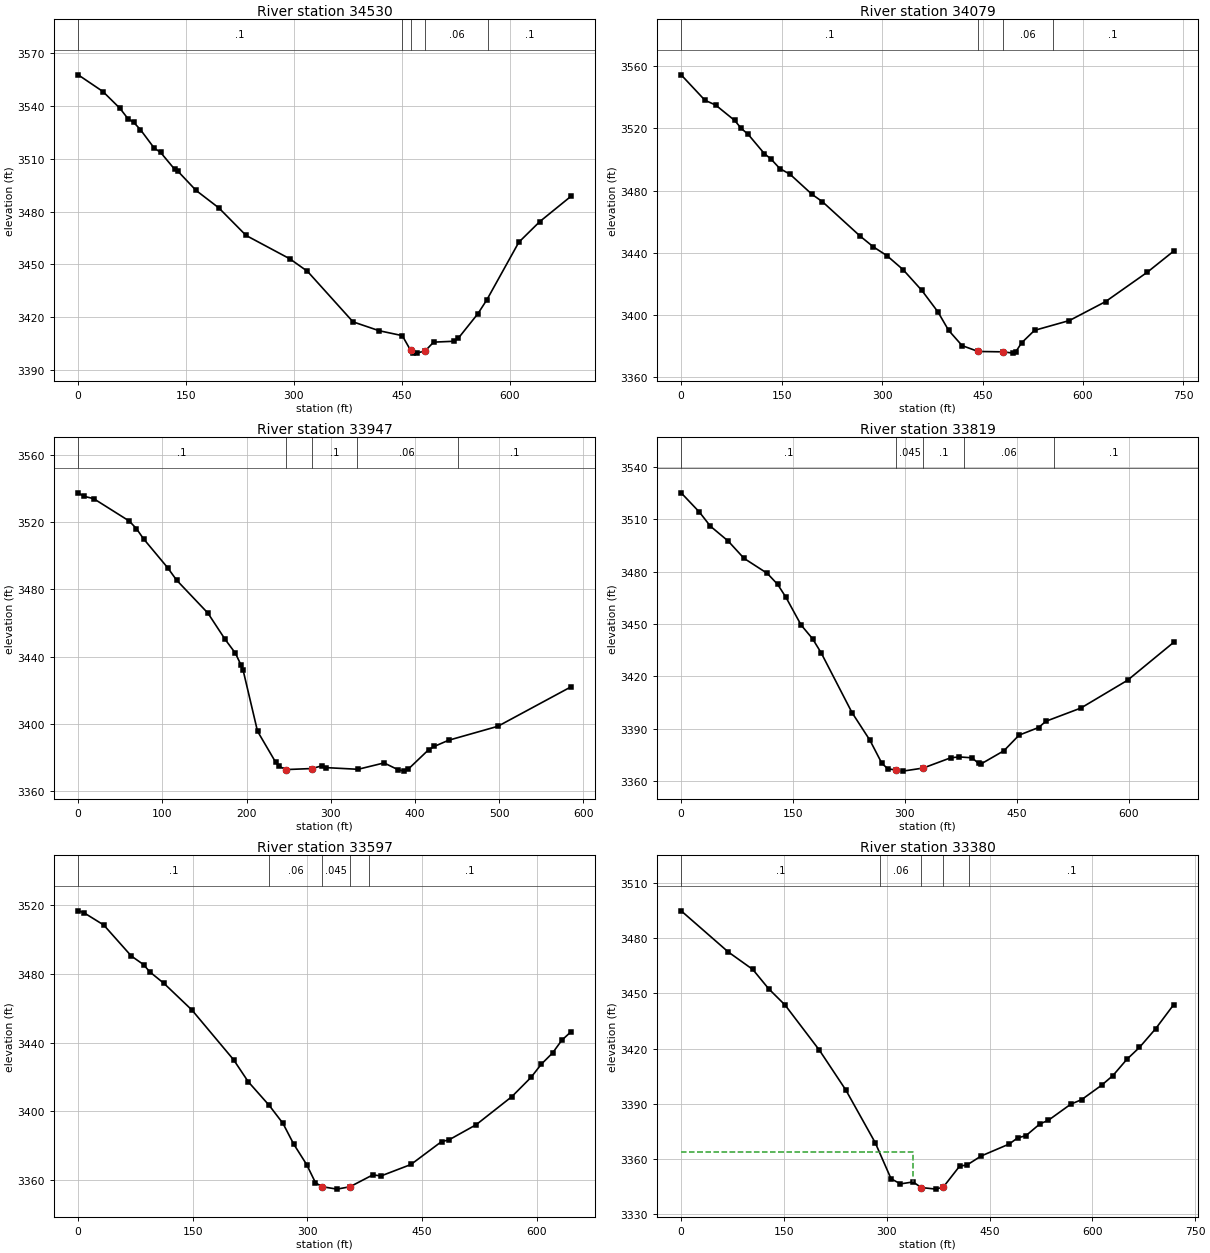
Type RM Length L Ch R = 1 ,34530   ,444,451.2,466.2
XS GIS Cut Line= 2
2175821.20750386473755.9846112462175243.21260766474123.799545194
#Sta/Elev= 30
       0 3557.78    34.4 3548.28    58.1 3538.72    69.3 3532.79    77.1 3530.79
    86.6 3526.58   105.5 3516.23   114.6 3513.65     134 3504.13   138.7 3502.94
   163.9 3492.04   195.6 3482.09   233.5 3466.42   294.3 3453.13   318.9    3446
   382.2 3417.27   418.5 3412.23   450.7 3409.43   462.3 3401.08   465.9 3399.56
   470.6 3399.48   482.6 3400.75   494.3 3405.73   522.8 3406.23   528.9 3408.09
   555.9 3421.92   568.5 3429.93   612.8 3462.57   641.9 3474.28   685.1 3488.62
#Mann= 5 ,-1,0
       0      .1       0     450     .06       0   462.3    .045       0
   482.6     .06       0     570      .1       0
Bank Sta=462.3,482.6
XS Rating Curve= 0 ,0
Exp/Cntr(USF)=0,0
Exp/Cntr=0.3,0.1

Type RM Length L Ch R = 1 ,34079   ,136.4,131.7,119.7
XS GIS Cut Line= 4
2175657.00440835473503.1118441572175492.80131283473621.338072926
2175151.25887417473642.6844753432175026.46452158473787.183199394
#Sta/Elev= 30
       0 3554.33    35.5    3538    51.5 3534.92    79.9 3525.03    89.7 3519.94
   100.2 3516.02   124.2 3503.72   133.9 3500.36   147.3 3494.13   162.6 3490.45
   195.2 3477.62     211 3472.81   267.1 3450.78   287.1 3443.78   307.2 3438.18
   331.2 3429.26   359.3 3415.87   383.3  3402.1   399.3 3390.23   419.4 3380.42
   443.4 3376.63   481.1 3376.39   495.5 3375.57   499.5 3376.37   508.3 3382.18
   527.6  3390.2   579.7 3396.51   633.6 3408.65     696 3427.55   735.5 3441.15
#Mann= 4 ,-1,0
       0      .1       0   443.4    .045       0   481.1     .06       0
  554.55      .1       0
Bank Sta=443.4,481.1
XS Rating Curve= 0 ,0
Exp/Cntr(USF)=0,0
Exp/Cntr=0.3,0.1

Type RM Length L Ch R = 1 ,33947   ,144.3,127.6,91.3
XS GIS Cut Line= 4
2175489.56635037 473368.823409652175369.53996819473481.348142939
2175223.25781492473536.3602347692175051.97016536473737.654479874
#Sta/Elev= 30
       0 3537.26     6.4 3535.26    18.4  3533.8    60.7 3520.48    69.2 3515.97
    77.6 3509.96   106.1 3492.86     117 3485.33   154.1 3465.78   174.5  3450.2
   186.8 3441.92   193.4 3434.91   195.9 3431.87     213 3395.61   234.4 3377.32
   238.6 3374.79   246.83372.834   277.7 3373.45   289.9 3375.12   294.2    3374
   332.4    3373   363.3 3376.78   380.3 3372.66   387.3 3371.91   391.7 3372.93
   416.4 3384.71   422.9 3386.58   439.9 3390.25   498.4 3398.54   585.1 3421.93
#Mann= 5 ,-1,0
       0      .1       0   246.8    .045       0   277.7      .1       0
  330.81     .06       0  450.81      .1       0
Bank Sta=246.8,277.7
XS Rating Curve= 0 ,0
Exp/Cntr(USF)=0,0
Exp/Cntr=0.3,0.1

Type RM Length L Ch R = 1 ,33819   ,210,222.5,238.7
XS GIS Cut Line= 5
2175328.03779235473219.858845347 2175194.6822702473352.103977138
2175177.37269905473532.6180762952175137.80796499473578.364800054
2175017.18484216473775.448078356
#Sta/Elev= 30
       0 3525.18    24.6 3514.09    39.2 3506.07    63.1 3497.53    84.3 3487.64
   115.5 3479.03   129.4 3472.73   140.6 3465.26   160.9  3449.4   176.2 3441.59
   187.8 3433.47   229.1 3399.27   253.2 3383.37   269.3 3370.08   277.3 3367.01
     2883366.354   297.3 3365.69   324.63367.449   361.7 3373.36   373.2 3373.82
   390.2 3373.32   398.8 3370.11   402.1 3369.78   432.9 3377.38   453.2 3386.31
   479.4 3390.68   489.2 3394.26   536.1 3401.84   598.7 3417.77   660.7 3439.55
#Mann= 5 ,-1,0
       0      .1       0     288    .045       0   324.6      .1       0
  379.15     .06       0  499.63      .1       0
Bank Sta=288,324.6
XS Rating Curve= 0 ,0
Exp/Cntr(USF)=0,0
Exp/Cntr=0.3,0.1

Type RM Length L Ch R = 1 ,33597   ,217.7,216.7,210.8
XS GIS Cut Line= 3
2175202.49023997473157.300125008 2174920.4963002473473.841558642
 2174894.1168266473692.930622569
#Sta/Elev= 30
       0 3516.58     7.2 3515.56    33.5 3508.32    69.5 3490.33    85.6 3485.31
    93.7  3481.1   112.3  3474.4   148.9 3458.91   203.4 3430.02   222.5 3417.28
     250 3403.49   267.9  3393.1     282 3381.03     299  3369.1   310.5 3358.58
   318.9 3356.29   338.7 3354.86   355.7 3356.25   385.5 3363.14   396.3 3362.53
   435.4 3369.18   475.6 3382.53   484.8 3383.39   520.7 3392.28   567.5 3408.63
   592.5 3419.79     606 3427.46   620.7 3433.97   632.8 3441.38   644.6 3446.21
#Mann= 5 ,-1,0
       0      .1       0     250     .06       0   318.9    .045       0
   355.7     .06       0     380      .1       0
Bank Sta=318.9,355.7
XS Rating Curve= 0 ,0
Exp/Cntr(USF)=0,0
Exp/Cntr=0.3,0.1

Type RM Length L Ch R = 1 ,33380   ,373.9,379.8,369.8
XS GIS Cut Line= 4
2175085.87925153473082.5692263422174826.23568425473258.137733741
2174771.83417492473338.5035998042174707.54148206473640.184697026
#Sta/Elev= 30
       0 3494.98    68.9 3472.54   104.6 3463.04   127.6 3452.59   151.7 3443.66
   201.9 3419.02   240.3 3397.42   283.2 3368.73   306.3  3349.1     320  3346.3
   338.5 3347.34   350.33344.319   371.8 3343.44   382.63344.575   406.4 3355.96
   417.3  3356.6   437.8 3361.48   478.7 3367.99   490.9 3371.31   503.2 3372.57
   523.5 3378.95   535.9 3380.93   568.6  3389.7   584.4 3392.16   613.6 3400.03
     630 3405.24   650.4  3414.1   668.7 3420.56   692.3 3430.73   718.9 3443.96
#Mann= 5 ,-1,0
       0      .1       0     290     .06       0   350.3    .045       0
   382.6     .06       0  420.48      .1       0
#XS Ineff= 2 , 0
          337.87 3363.81
Permanent Ineff=
       F       F
Bank Sta=350.3,382.6
XS Rating Curve= 0 ,0
Exp/Cntr(USF)=0,0
Exp/Cntr=0.3,0.1

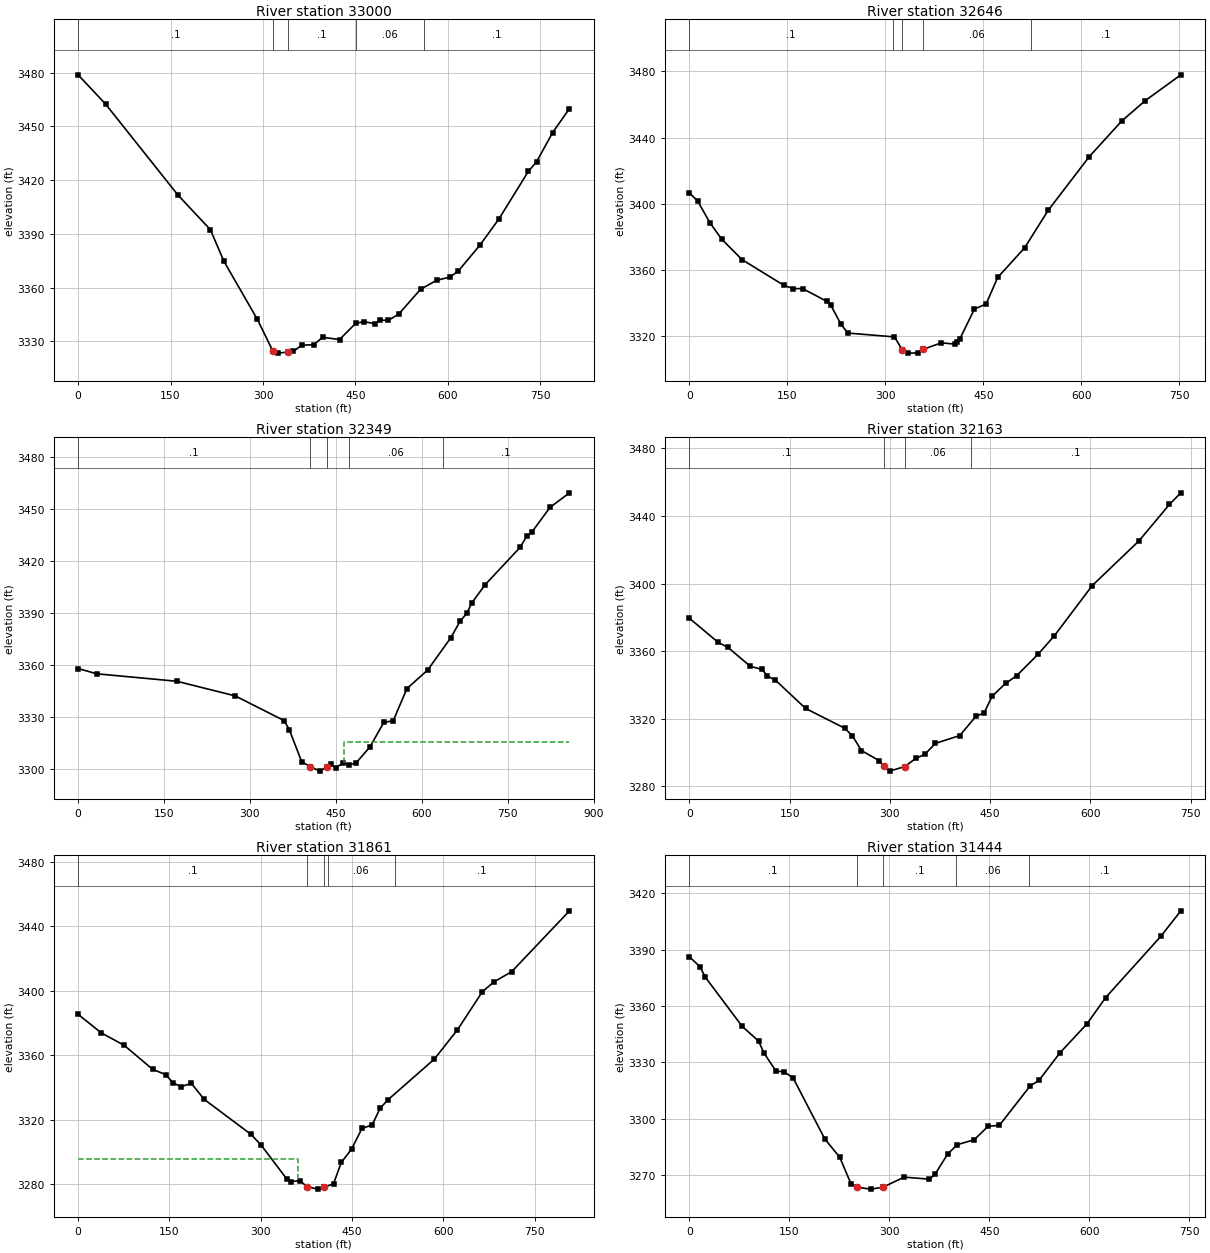
Type RM Length L Ch R = 1 ,33000   ,361.3,354.5,345.6
XS GIS Cut Line= 3
2174810.16251104472811.7980776062174591.32007576473003.439758218
2174384.84161987473465.852587566
#Sta/Elev= 30
       0 3478.82    44.6 3462.48   162.1 3411.68   214.6 3392.41   236.6 3374.75
   290.9 3342.32   315.8 3324.77   324.9  3323.5   340.83324.159   349.1 3324.48
   362.9 3327.89   382.4 3328.22   396.7 3332.32   424.2 3331.09   450.5 3340.15
   464.2 3341.07   481.2 3339.94   489.9 3341.94   503.6 3341.78   520.6 3345.41
   555.6 3359.11   581.9 3364.17   603.5 3365.95     617 3369.37   651.8 3383.68
   682.7 3398.33   730.7 3425.01     744 3430.34     770 3446.63   797.3 3459.99
#Mann= 5 ,-1,0
       0      .1       0   315.8    .045       0   340.8      .1       0
  450.89     .06       0  560.89      .1       0
Bank Sta=315.8,340.8
XS Rating Curve= 0 ,0
Exp/Cntr(USF)=0,0
Exp/Cntr=0.3,0.1

Type RM Length L Ch R = 1 ,32646   ,284.9,296.6,304.8
XS GIS Cut Line= 4
2174465.94949171472746.8225137312174235.28981115472940.316872994
2174235.02785496473051.4382483082174079.07841004473353.754674938
#Sta/Elev= 30
       0 3406.49    12.8  3401.4    31.3 3388.44    49.3 3378.51    80.6 3366.11
   144.9 3350.48   158.9  3348.6   173.3  3348.6   210.2  3340.9   216.4 3338.59
     232 3327.03   242.5 3321.69   313.9 3319.37   325.9 3311.49   333.9 3309.55
   349.9 3309.61   356.9 3311.75   385.9  3315.8   405.9    3315   409.9 3316.09
   414.2  3318.3   436.4 3336.26   454.2 3339.29     472 3355.37   513.2 3373.27
   549.2 3395.91   612.2 3428.45     662 3450.05   697.7 3462.26   752.4 3477.94
#Mann= 5 ,-1,0
       0      .1       0  311.07     .06       0   325.9    .045       0
   356.9     .06       0  522.19      .1       0
Bank Sta=325.9,356.9
XS Rating Curve= 0 ,0
Exp/Cntr(USF)=0,0
Exp/Cntr=0.3,0.1

Type RM Length L Ch R = 1 ,32349   ,216,186.5,178.3
XS GIS Cut Line= 4
2174103.52843196472445.0573223312174093.87277651 472627.18717939
2173955.96458661472897.8967141882173910.54835525473266.806327587
#Sta/Elev= 30
       0 3358.11    32.2 3355.08   172.4 3350.77   274.4 3342.34   359.7  3328.1
   368.7  3322.9   390.3 3304.52   405.2 3301.57   422.5 3299.04   434.9 3301.59
   441.7 3302.92   449.5 3301.07   462.9 3303.65   473.6 3302.68   485.7 3303.91
   509.7 3313.04   533.8 3327.16     550 3327.94   574.1 3346.55   610.4 3357.27
   650.7 3375.83   666.8 3385.25   678.9 3390.01     687 3395.72   710.8 3406.41
   771.6 3427.82   783.2 3434.21   791.8 3436.46     824 3450.88   857.9 3459.24
#Mann= 5 ,-1,0
       0      .1       0   405.2    .045       0   434.9      .1       0
  472.39     .06       0   636.2      .1       0
#XS Ineff= 2 , 0
                          464.72         3315.53
Permanent Ineff=
       F       F
Bank Sta=405.2,434.9
XS Rating Curve= 0 ,0
Exp/Cntr(USF)=0,0
Exp/Cntr=0.3,0.1

Type RM Length L Ch R = 1 ,32163   ,298.4,301.4,304.2
XS GIS Cut Line= 4
2173709.17226018 472543.448447352173760.72951974472777.642366201
2173812.24224256472877.2476680082173868.34517077473256.391636243
#Sta/Elev= 30
       0  3379.4    42.7 3365.28    57.7 3362.18    91.2 3350.98   108.3  3349.3
   116.5 3345.39   128.7 3342.81   173.8 3326.11   232.2 3314.45   243.8 3309.95
   257.3 3301.22   284.3 3295.17   290.8 3291.87   299.5 3289.06   322.2 3291.77
   338.4 3296.54   351.9 3298.91     368 3305.46   404.4  3310.1   428.7 3321.51
   440.8 3323.43     453 3333.48   473.2    3341   489.4 3345.43   521.7 3358.22
     546 3369.12   602.6 3398.77   672.4 3425.15   718.1 3446.74   735.2 3453.62
#Mann= 4 ,-1,0
       0      .1       0   290.8    .045       0   322.2     .06       0
  421.94      .1       0
Bank Sta=290.8,322.2
XS Rating Curve= 0 ,0
Exp/Cntr(USF)=0,0
Exp/Cntr=0.3,0.1

Type RM Length L Ch R = 1 ,31861   ,416.2,417.8,415.6
XS GIS Cut Line= 2
2173375.41894284472561.7714371982173645.44181102473322.579113073
#Sta/Elev= 30
       0 3385.29    38.1 3373.79    75.8 3366.06   122.3 3351.25   143.7 3347.93
   156.4 3342.68   169.1 3340.53   186.1 3342.45   207.3 3332.53   283.8 3310.95
   300.9 3304.13   343.2 3283.03   349.1 3281.64   364.4  3282.1     376 3278.49
   394.1 3276.93   404.2 3278.11   419.6 3280.25   432.4 3293.47   449.3 3301.76
   466.3 3314.52   483.2 3316.81     496 3326.92   508.7  3332.2   585.1 3357.47
   623.3 3375.72   664.2 3399.33     683 3405.36   712.4 3411.78   807.3 3449.47
#Mann= 5 ,-1,0
       0      .1       0     376    .045       0   404.2      .1       0
     410     .06       0     520      .1       0
#XS Ineff= 2 , 0
          361.14 3295.74
Permanent Ineff=
       F       F
Bank Sta=376,404.2
XS Rating Curve= 0 ,0
Exp/Cntr(USF)=0,0
Exp/Cntr=0.3,0.1

Type RM Length L Ch R = 1 ,31444   ,479.4,470.4,455.4
XS GIS Cut Line= 3
2173023.29452691472762.4641094912173180.19970707473249.599959512
2173322.50905651473424.749928058
#Sta/Elev= 30
       0 3386.21    15.5 3381.05    23.9 3375.31    79.1 3349.17   103.7 3341.33
   112.1 3334.77     130 3325.24   141.5 3325.02   155.4 3321.79   203.1 3289.14
   225.6 3279.33   242.4 3265.27   250.8 3263.44   271.8 3262.39   289.9 3263.33
   322.2 3268.78   360.1 3267.71   368.5 3270.24   387.5 3281.12   402.1 3286.11
   427.3 3288.72   448.3 3295.91   465.1 3296.37   511.3 3317.39   524.4 3320.31
   556.1 3335.07   596.8 3350.58   624.6  3364.5   707.7 3397.27   737.5 3410.76
#Mann= 5 ,-1,0
       0      .1       0   250.8    .045       0   289.9      .1       0
     400     .06       0     510      .1       0
Bank Sta=250.8,289.9
XS Rating Curve= 0 ,0
Exp/Cntr(USF)=0,0
Exp/Cntr=0.3,0.1