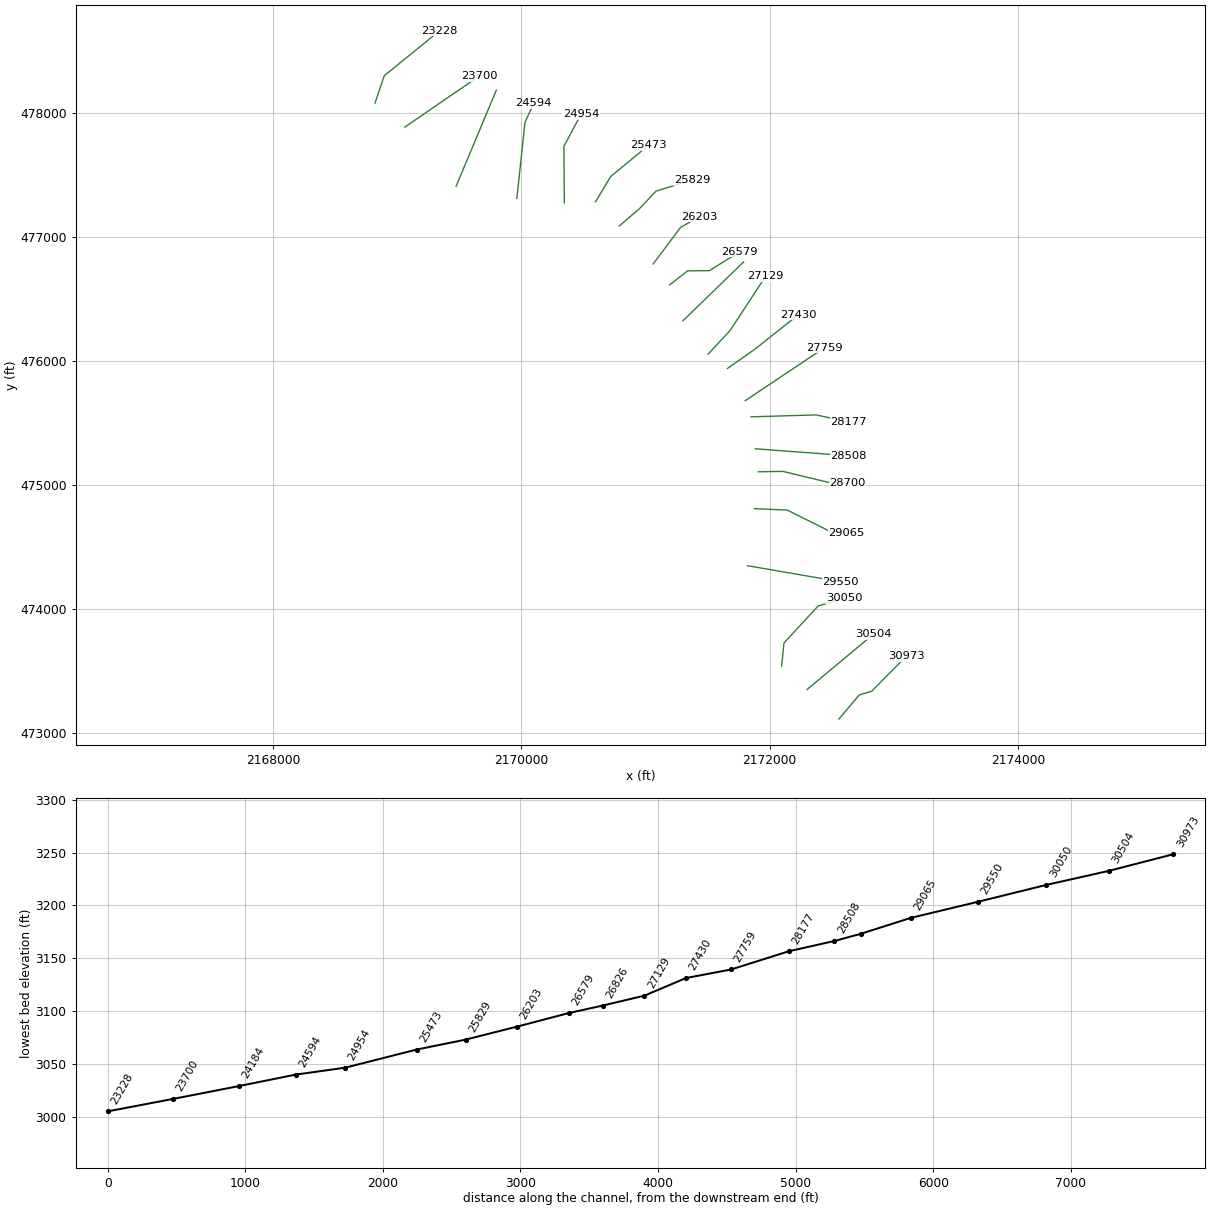
HEC-RAS study MFWILLIAMSRV.prj: MFWILLIAMSRV

--- MFWILLIAMSRV.g01 (geometry) --- (continued)

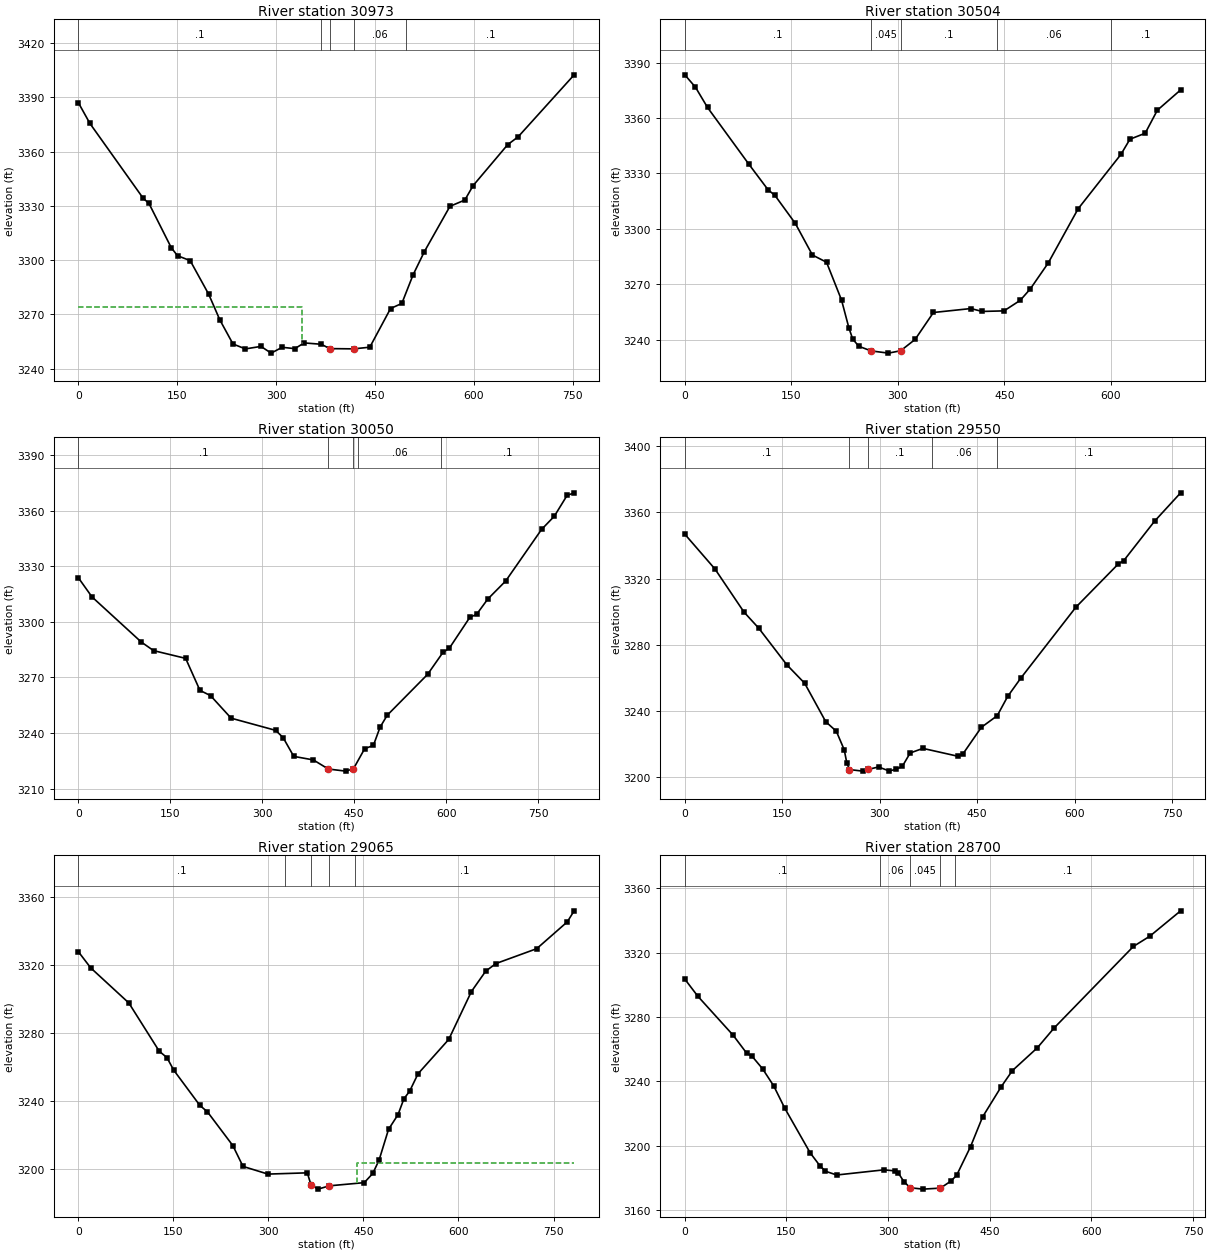
Type RM Length L Ch R = 1 ,30973   ,465.4,469.4,447.3
XS GIS Cut Line= 4
2172558.84338488473115.7520171692172722.79291864473309.133409923
2172822.66370121473339.2945039042173099.92263815473619.969163834
#Sta/Elev= 30
       0 3387.05    17.6 3375.52    98.4 3334.17   107.2 3331.29     141 3306.84
   150.5 3302.38   169.7 3299.69   197.8  3281.1   214.8 3266.85   234.7 3253.57
   253.5 3250.85   277.1 3252.24   292.6 3248.52   309.3 3251.75   328.5    3251
   342.7 3254.17   368.7 3253.42   381.53251.017   417.83250.878   442.3  3251.8
   473.8 3273.19   490.9 3276.01     508 3291.84   525.1 3304.65   563.9  3329.7
   586.5 3333.18   599.1 3341.17   651.6 3363.83   667.4 3368.14   752.4 3402.42
#Mann= 5 ,-1,0
       0      .1       0  367.85     .06       0   381.5    .045       0
   417.8     .06       0  497.85      .1       0
#XS Ineff= 2 , 0
          339.32 3273.83
Permanent Ineff=
       F       F
Bank Sta=381.5,417.8
XS Rating Curve= 0 ,0
Exp/Cntr(USF)=0,0
Exp/Cntr=0.3,0.1

Type RM Length L Ch R = 1 ,30504   ,444.1,454.1,450.7
XS GIS Cut Line= 2
2172302.62538549473353.5952533362172839.02216417473800.592568898
#Sta/Elev= 30
       0 3383.39      15  3376.7      32 3365.72    90.5 3334.87   117.2  3321.2
     127 3318.09   155.6 3302.98   179.7 3285.87   199.6 3281.95   220.7 3261.49
   231.1 3246.37   236.5 3240.33   245.1 3236.46   262.4 3233.96   286.8 3232.76
     304 3234.06   324.3 3240.17   350.1 3254.75   402.9 3256.89   418.6 3255.32
   449.5 3255.63   472.3 3261.32   486.5  3267.5   511.7 3281.51   553.9  3310.9
   614.3 3340.41   626.8 3348.53   648.3 3351.78   665.4 3364.22   698.2 3375.23
#Mann= 5 ,-1,0
       0      .1       0   262.4    .045       0     304      .1       0
     440     .06       0     600      .1       0
Bank Sta=262.4,304
XS Rating Curve= 0 ,0
Exp/Cntr(USF)=0,0
Exp/Cntr=0.3,0.1

Type RM Length L Ch R = 1 ,30050   ,519.3,500.1,478.6
XS GIS Cut Line= 4
2172097.33502653473542.976156828 2172115.9264659 473728.03304547
 2172391.4045258474026.6272522662172599.23091036474088.057454776
#Sta/Elev= 30
       0 3323.77    22.3 3313.42   102.7 3289.09   122.8 3284.46   175.1 3280.28
   198.4 3263.03   215.8 3260.17   249.3 3248.03     322 3241.46   334.2 3237.52
   351.5 3227.43   383.5 3225.52   407.8 3220.62   436.1 3219.48   448.8 3220.69
   467.2 3231.58   481.4 3233.33   492.3 3243.15     504 3249.62   569.8 3271.63
   594.9 3283.49   605.6 3285.89   638.9 3302.47   649.7 3303.96   668.1 3312.28
   697.3 3322.01   755.9 3349.84   776.6 3356.92   797.4 3368.13     809 3369.55
#Mann= 5 ,-1,0
       0      .1       0   407.8    .045       0   448.8      .1       0
  455.99     .06       0  592.25      .1       0
Bank Sta=407.8,448.8
XS Rating Curve= 0 ,0
Exp/Cntr(USF)=0,0
Exp/Cntr=0.3,0.1

Type RM Length L Ch R = 1 ,29550   ,489,484.9,478.8
XS GIS Cut Line= 2
2171822.35948666474350.8445750232172574.40966411474221.124129568
#Sta/Elev= 30
       0 3346.87    46.5 3325.76    91.1 3299.72   113.8 3289.97   157.1 3267.76
   184.5 3256.62     217 3233.31   233.2 3227.58   245.4 3216.34   249.4 3208.32
   253.5 3204.35   273.8 3203.41   281.9 3204.43   298.2 3205.93   314.6 3203.51
     325  3204.5   334.7 3206.23   346.9 3214.39   366.5 3217.18   419.9 3212.46
     428 3213.76   456.5 3229.94   480.9 3236.97     497 3248.64   517.3 3259.78
   601.9 3302.62   667.5 3328.94   675.6 3330.83   723.1 3354.74   763.2 3371.91
#Mann= 5 ,-1,0
       0      .1       0   253.5    .045       0   281.9      .1       0
     380     .06       0     480      .1       0
Bank Sta=253.5,281.9
XS Rating Curve= 0 ,0
Exp/Cntr(USF)=0,0
Exp/Cntr=0.3,0.1

Type RM Length L Ch R = 1 ,29065   ,357,364.9,356
XS GIS Cut Line= 4
2171876.54650818474810.6132424582172142.55552291474799.119025773
2172476.47614649474632.7612572412172619.04893243474618.227477054
#Sta/Elev= 30
       0 3327.76    19.6 3318.21    79.7 3297.63   127.7 3269.29   139.8 3265.55
   150.7  3258.1   191.8 3237.47   203.8 3233.67   243.9 3213.84   259.9 3201.63
   299.3 3197.11   361.4 3197.85   367.3 3190.72   378.3 3188.28   396.2 3190.22
   451.3 3192.09   464.7 3197.46   474.7 3205.34   489.6 3223.38   504.6 3232.04
   513.9 3241.37   522.8 3245.71   536.2 3256.05   584.6 3276.19   620.4 3304.33
     643 3316.31   659.1 3320.77   723.5 3329.51   771.7 3345.24   782.6 3351.74
#Mann= 5 ,-1,0
       0      .1       0  326.26     .06       0   367.3    .045       0
   396.2     .06       0  436.26      .1       0
#XS Ineff= 2 , 0
                          439.15         3203.41
Permanent Ineff=
       F       F
Bank Sta=367.3,396.2
XS Rating Curve= 0 ,0
Exp/Cntr(USF)=0,0
Exp/Cntr=0.3,0.1

Type RM Length L Ch R = 1 ,28700   ,188,191.3,196.2
XS GIS Cut Line= 4
2171908.90157255475107.8677746642172107.58731812475111.151836574
2172467.19209729475024.1241959522172629.75316185475014.272010222
#Sta/Elev= 30
       0 3303.56    19.3 3292.88    71.3 3268.72    91.3 3257.57    99.3 3255.63
   114.7  3247.9   131.3 3237.18   147.3 3223.57     185 3195.69   199.3 3187.71
   207.5 3184.28   224.1 3181.94     294 3185.15   310.4 3184.47   314.6 3183.41
   323.4 3177.79   332.6 3174.01   351.6 3173.17   377.2  3173.8   392.3 3178.06
     401 3181.67   421.6 3199.51   439.4 3217.99   466.8 3236.69   483.3 3246.72
   520.3 3260.96     545 3273.24   661.9 3323.83   686.1 3330.18   731.6 3345.94
#Mann= 5 ,-1,0
       0      .1       0  288.71     .06       0   332.6    .045       0
   377.2     .06       0  398.71      .1       0
Bank Sta=332.6,377.2
XS Rating Curve= 0 ,0
Exp/Cntr(USF)=0,0
Exp/Cntr=0.3,0.1

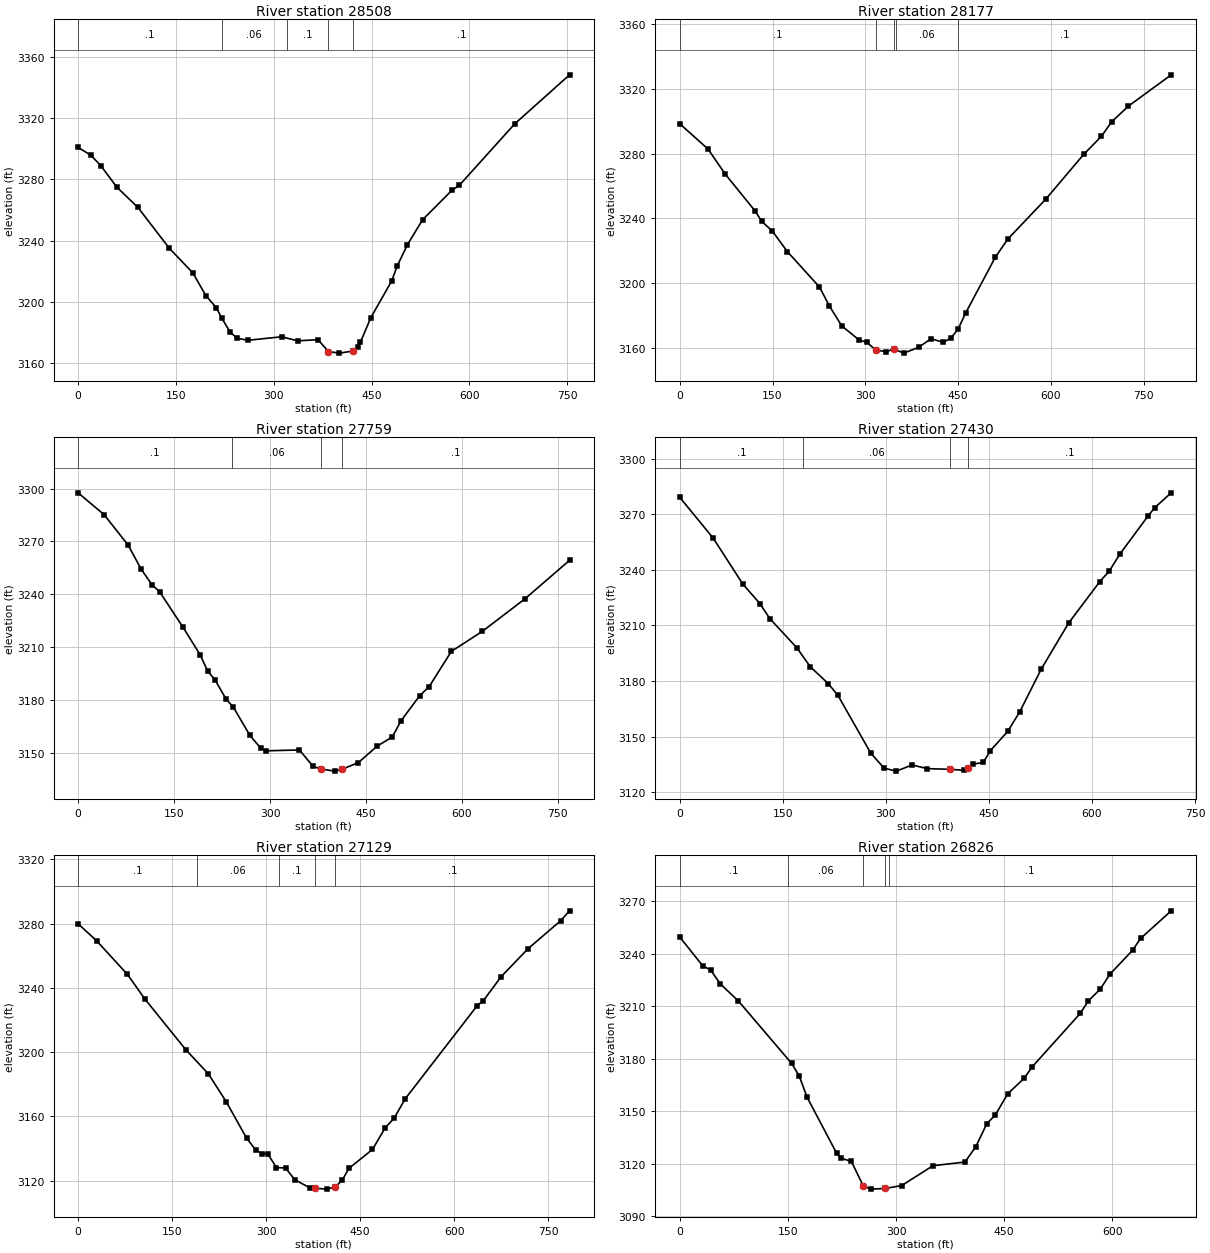
Type RM Length L Ch R = 1 ,28508   ,328.1,331.5,336
XS GIS Cut Line= 2
  2171884.752382475293.1703593382172636.08885274475237.201728335
#Sta/Elev= 30
       0 3300.82    19.5 3295.81    35.5 3288.54    59.2 3274.95    91.7 3261.62
   139.8 3234.96   175.9 3218.82     196 3203.89     212 3196.03     220  3189.4
   233.4 3179.92   244.1  3176.1   260.1 3174.78   312.3 3177.09   336.4 3174.42
   367.8 3175.18   383.83167.419   400.5 3166.39   421.53167.767   428.6 3170.41
   432.8 3173.51   448.7 3189.54   480.8 3213.65   489.1 3223.27   504.8 3237.21
   528.1 3253.59     573 3272.81   584.5 3276.12   669.3 3316.24   753.4 3348.31
#Mann= 5 ,-1,0
       0      .1       0     220     .06       0     320      .1       0
   383.8    .045       0   421.5      .1       0
Bank Sta=383.8,421.5
XS Rating Curve= 0 ,0
Exp/Cntr(USF)=0,0
Exp/Cntr=0.3,0.1

Type RM Length L Ch R = 1 ,28177   ,405.8,418,428.8
XS GIS Cut Line= 3
2171850.46323195475550.7038495332172375.18163774475566.165172149
2172638.30483864475509.068108884
#Sta/Elev= 30
       0 3298.45    45.7 3282.81    73.7 3267.22   121.8 3244.51   132.3  3238.2
   149.8 3232.05   173.8 3219.47   225.8 3197.55   241.8 3185.85   261.8 3173.52
   289.8  3164.8   301.8 3163.44   316.7 3158.64   333.9 3157.52   345.83159.302
   361.9 3156.67   385.9 3160.21   405.9 3165.55   425.9  3163.4   437.9 3165.82
   449.9 3171.58   461.9 3181.36   509.9 3215.91   530.2 3227.19   591.5 3251.84
   652.8  3279.5   681.5 3290.72   697.9  3299.6     725 3309.34   794.2 3328.69
#Mann= 5 ,-1,0
       0      .1       0   316.7    .045       0   345.8      .1       0
     350     .06       0     450      .1       0
Bank Sta=316.7,345.8
XS Rating Curve= 0 ,0
Exp/Cntr(USF)=0,0
Exp/Cntr=0.3,0.1

Type RM Length L Ch R = 1 ,27759   ,325.2,328.6,328.8
XS GIS Cut Line= 2
2171803.81159142475680.9365780032172442.56163297476107.864626336
#Sta/Elev= 30
       0 3297.57    40.8 3285.12    78.3 3267.82    98.5 3254.23   115.9 3245.15
   127.3 3241.44     164 3221.21   190.8 3205.55   202.5 3196.34   213.8 3191.45
   231.1 3180.54   242.7 3175.79   268.6 3159.78   285.9 3152.35   293.9 3151.01
     346 3151.51   367.5 3142.11   380.5 3140.59   401.3 3139.48   412.8 3140.52
   438.3 3144.37   467.1 3153.55   491.2 3158.92   505.1 3168.22   533.9 3182.26
   548.9 3187.53   583.5 3207.49     632 3218.88   698.7  3237.4   768.3 3259.23
#Mann= 4 ,-1,0
       0      .1       0     240     .06       0   380.5    .045       0
   412.8      .1       0
Bank Sta=380.5,412.8
XS Rating Curve= 0 ,0
Exp/Cntr(USF)=0,0
Exp/Cntr=0.3,0.1

Type RM Length L Ch R = 1 ,27430   ,295,301.7,307.6
XS GIS Cut Line= 3
2171660.91931889475940.5909455312171881.59168167476096.211905563
2172230.86954466  476372.2973921
#Sta/Elev= 30
       0 3279.16    48.7 3257.13    91.7 3232.38   116.6 3221.83   131.2 3213.65
   170.4 3197.94     190  3187.7   216.2 3178.56   230.1 3172.29     278 3141.07
   297.4 3132.95   315.3 3131.35   338.1 3134.68     360 3132.71   393.8 3132.31
   413.5 3131.81   419.9 3133.22   426.3 3135.09   441.6 3136.01   452.2 3142.47
   477.3 3152.82   494.7  3163.3     526 3186.37   565.9 3211.28   611.4 3233.72
   625.1 3239.35   640.4 3248.46   681.2 3268.94   691.4 3273.65   715.2  3281.6
#Mann= 4 ,-1,0
       0      .1       0     180     .06       0   393.8    .045       0
   419.9      .1       0
Bank Sta=393.8,419.9
XS Rating Curve= 0 ,0
Exp/Cntr(USF)=0,0
Exp/Cntr=0.3,0.1

Type RM Length L Ch R = 1 ,27129   ,308.5,303.1,299.7
XS GIS Cut Line= 3
2171504.02497524476055.505211787 2171681.6357545476246.272345068
2171968.44427213476684.378933914
#Sta/Elev= 30
       0 3279.93    29.6 3269.29    78.8 3248.36   106.1  3233.3   171.7  3201.6
   207.9 3186.47   236.2 3169.25   268.9 3146.41   283.2 3139.23   292.8 3136.86
   302.4 3136.84   316.6 3128.09   331.1 3127.87   345.6 3120.61   369.3 3115.62
   378.83115.266   396.7  3114.7   410.43115.959   421.9 3120.55   432.2 3127.63
   469.8 3139.39     490 3152.87   504.4 3158.86   521.7 3170.77     637 3228.98
   646.6 3232.01   675.3 3247.06   718.3  3264.5   770.2 3281.86   784.3 3287.99
#Mann= 5 ,-1,0
       0      .1       0     190     .06       0  320.65      .1       0
   378.8    .045       0   410.4      .1       0
Bank Sta=378.8,410.4
XS Rating Curve= 0 ,0
Exp/Cntr(USF)=0,0
Exp/Cntr=0.3,0.1

Type RM Length L Ch R = 1 ,26826   ,261.7,246.8,230.2
XS GIS Cut Line= 2
2171301.35011915476324.6127124132171790.67534378476799.159658444
#Sta/Elev= 30
       0 3249.56    31.8 3233.15    42.9 3230.67    56.1 3222.83    81.3 3212.99
   155.2 3177.25   165.5 3170.24   176.7 3157.84   217.4 3126.03     223  3123.1
     238 3121.22   254.7 3107.07   265.1 3105.34   285.3 3105.73   307.9  3107.4
   351.3 3118.75   395.6 3120.83   410.7 3129.69     426 3142.88   437.5  3147.7
     455 3159.91   477.6 3168.73   488.9 3175.33   555.6 3205.96   566.7 3213.04
   583.4 3219.84   596.4 3228.19     628 3241.99   639.2 3248.77   681.6 3264.57
#Mann= 5 ,-1,0
       0      .1       0     150     .06       0   254.7    .045       0
   285.3     .06       0     290      .1       0
Bank Sta=254.7,285.3
XS Rating Curve= 0 ,0
Exp/Cntr(USF)=0,0
Exp/Cntr=0.3,0.1

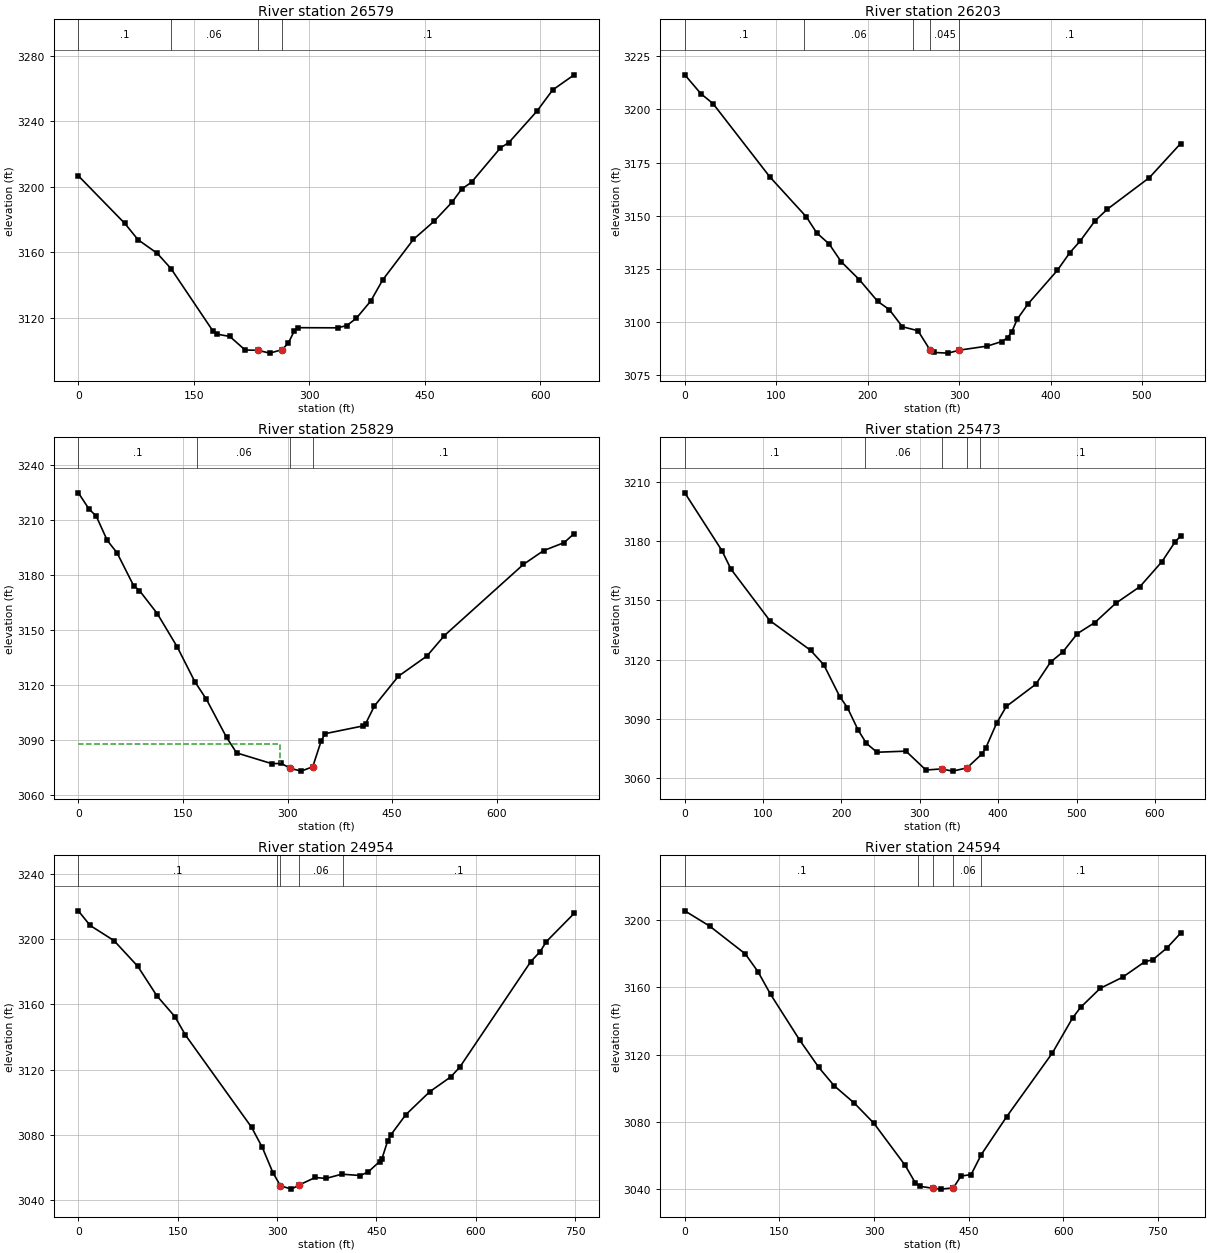
Type RM Length L Ch R = 1 ,26579   ,355.6,375.8,394.2
XS GIS Cut Line= 4
2171194.23324922476614.3562729622171339.81620639476727.359533867
2171514.78086314476728.8375636512171755.95478219476879.952867359
#Sta/Elev= 30
       0 3206.72    60.4 3177.56    77.5 3167.62   102.5 3159.27   120.3 3149.96
   174.6 3111.89   180.7 3109.78   196.7 3108.42   216.7 3100.09   232.7 3099.98
   248.7 3098.22   264.7 3100.36   272.7 3104.41   280.7 3111.99   284.7 3113.79
   336.7  3113.7   348.7 3115.11   360.9 3119.49   379.8 3130.14   395.3 3143.05
   435.2 3167.83   462.1 3178.96   485.3 3190.55   497.8 3198.58   510.6  3202.8
   548.2 3223.83   559.2 3227.09   595.6 3246.31     616 3259.27   643.9 3268.51
#Mann= 4 ,-1,0
       0      .1       0     120     .06       0   232.7    .045       0
   264.7      .1       0
Bank Sta=232.7,264.7
XS Rating Curve= 0 ,0
Exp/Cntr(USF)=0,0
Exp/Cntr=0.3,0.1

Type RM Length L Ch R = 1 ,26203   ,376.8,374.2,371.9
XS GIS Cut Line= 3
 2171061.6135997476782.7393488932171283.21904193477078.289386356
2171433.95696122477163.064212535
#Sta/Elev= 30
       0 3216.25    17.6 3207.38    30.9  3202.7      93 3168.27     133 3149.44
   144.3 3141.94   157.9 3136.71     171 3128.42     191 3119.89     211 3109.73
   223.6  3105.9     238 3097.81     255 3095.95     268 3087.05     273 3085.71
     288 3085.41   300.43086.819     331 3088.73   346.4 3090.83     353 3092.63
   357.7 3095.47   363.6 3101.35   375.3 3108.49   407.5 3124.35     421 3132.57
   432.4  3138.1   448.7 3147.64   462.3 3153.13   508.2 3167.94   542.3 3183.95
#Mann= 5 ,-1,0
       0      .1       0     130     .06       0     250      .1       0
     268    .045       0   300.4      .1       0
Bank Sta=268,300.4
XS Rating Curve= 0 ,0
Exp/Cntr(USF)=0,0
Exp/Cntr=0.3,0.1

Type RM Length L Ch R = 1 ,25829   ,356.6,355.9,350.7
XS GIS Cut Line= 4
2170788.65305389477089.038138555  2170952.132337477229.163238357
2171084.01478387 477369.288338162171373.88141189477458.583744897
#Sta/Elev= 30
       0 3224.99    15.2 3216.22    25.7 3212.24    41.5    3199    55.5 3192.25
    79.2 3174.39    87.7 3171.62   113.2 3159.08   141.6 3141.04   167.1 3121.91
   183.8 3112.21   212.5 3091.56     227 3083.04   277.6 3077.15   291.2 3077.29
   304.23074.558   319.7 3073.09   336.2 3075.49   348.4 3089.73     354 3093.54
   407.9 3097.73   412.1 3099.04   424.7 3108.68     459 3124.87     500 3135.93
   525.1 3147.11   638.3 3185.92   667.4 3193.47   696.7  3197.8   711.1 3202.76
#Mann= 4 ,-1,0
       0      .1       0     170     .06       0   304.2    .045       0
   336.2      .1       0
#XS Ineff= 2 , 0
          289.56 3087.98
Permanent Ineff=
       F       F
Bank Sta=304.2,336.2
XS Rating Curve= 0 ,0
Exp/Cntr(USF)=0,0
Exp/Cntr=0.3,0.1

Type RM Length L Ch R = 1 ,25473   ,500.4,518.5,537.6
XS GIS Cut Line= 3
 2170596.9188394477283.5587902072170718.72788154477486.608764857
2171024.11817258477738.833944502
#Sta/Elev= 30
       0 3204.35    47.3  3175.2    58.9  3165.8   108.5 3139.79   160.5 3124.78
   177.4 3117.44   197.8 3101.36   207.6 3095.75   221.1 3084.57   231.8 3077.72
   245.3 3073.24   282.3 3073.79   307.8 3064.25   327.7  3064.8   341.9 3063.69
   360.2 3065.32   378.9 3072.23   383.9 3075.13   397.9 3087.83   410.4 3096.39
   448.1 3107.62   466.9 3118.81   482.5 3123.89     501 3133.17   523.5 3138.81
   549.9 3148.46   581.1 3156.99     609 3169.54     626 3179.64   632.9 3182.55
#Mann= 5 ,-1,0
       0      .1       0     230     .06       0   327.7    .045       0
   360.2     .06       0  376.78      .1       0
Bank Sta=327.7,360.2
XS Rating Curve= 0 ,0
Exp/Cntr(USF)=0,0
Exp/Cntr=0.3,0.1

Type RM Length L Ch R = 1 ,24954   ,362.8,360.6,359.4
XS GIS Cut Line= 3
2170345.68810327477275.3486354312170342.40404136477730.191210001
2170480.33464159477989.632100911
#Sta/Elev= 30
       0 3217.46    17.8 3208.48    53.8 3199.19    89.8 3183.36   118.5 3165.32
   145.8  3152.5   161.8 3141.14   261.5 3084.59   277.8 3072.18   293.8  3056.7
   305.1 3048.64   321.8 3046.56   333.8 3049.18   357.8 3053.72   373.8 3053.12
   397.8 3055.73   425.8 3054.92   437.8 3057.14   454.9 3063.49   458.4 3065.14
   467.2  3076.3   471.8 3079.83   494.5 3092.28   530.7  3106.4   562.4 3115.49
     576 3121.47   683.2 3186.28   697.2 3192.35   706.8  3198.6   748.7 3215.89
#Mann= 5 ,-1,0
       0      .1       0     300     .06       0   305.1    .045       0
   333.8     .06       0     400      .1       0
Bank Sta=305.1,333.8
XS Rating Curve= 0 ,0
Exp/Cntr(USF)=0,0
Exp/Cntr=0.3,0.1

Type RM Length L Ch R = 1 ,24594   ,417.1,410.2,399.8
XS GIS Cut Line= 3
2169963.09489073477309.8312854892170028.77612893477925.592893661
   2170099.38346478076.659741533
#Sta/Elev= 30
       0 3205.48    39.6 3196.34    95.9 3179.87     116 3169.28   136.1 3155.75
   182.1 3128.63   212.5 3112.31   236.7 3101.49   268.9 3091.07   299.8 3079.13
   349.3 3054.14   365.4 3043.72   373.5 3041.62   393.6 3040.45   405.6 3039.98
   425.7 3040.72   425.7 3040.73   437.8 3047.75   453.9 3048.63     470 3060.52
   510.2 3083.04   582.6  3120.9   614.8  3141.8   627.5  3148.1   658.5 3159.38
   693.9 3165.97   729.2 3175.19   741.9 3176.39   764.5 3183.48     786 3192.18
#Mann= 5 ,-1,0
       0      .1       0     370     .06       0   393.6    .045       0
   425.7     .06       0     470      .1       0
Bank Sta=393.6,425.7
XS Rating Curve= 0 ,0
Exp/Cntr(USF)=0,0
Exp/Cntr=0.3,0.1

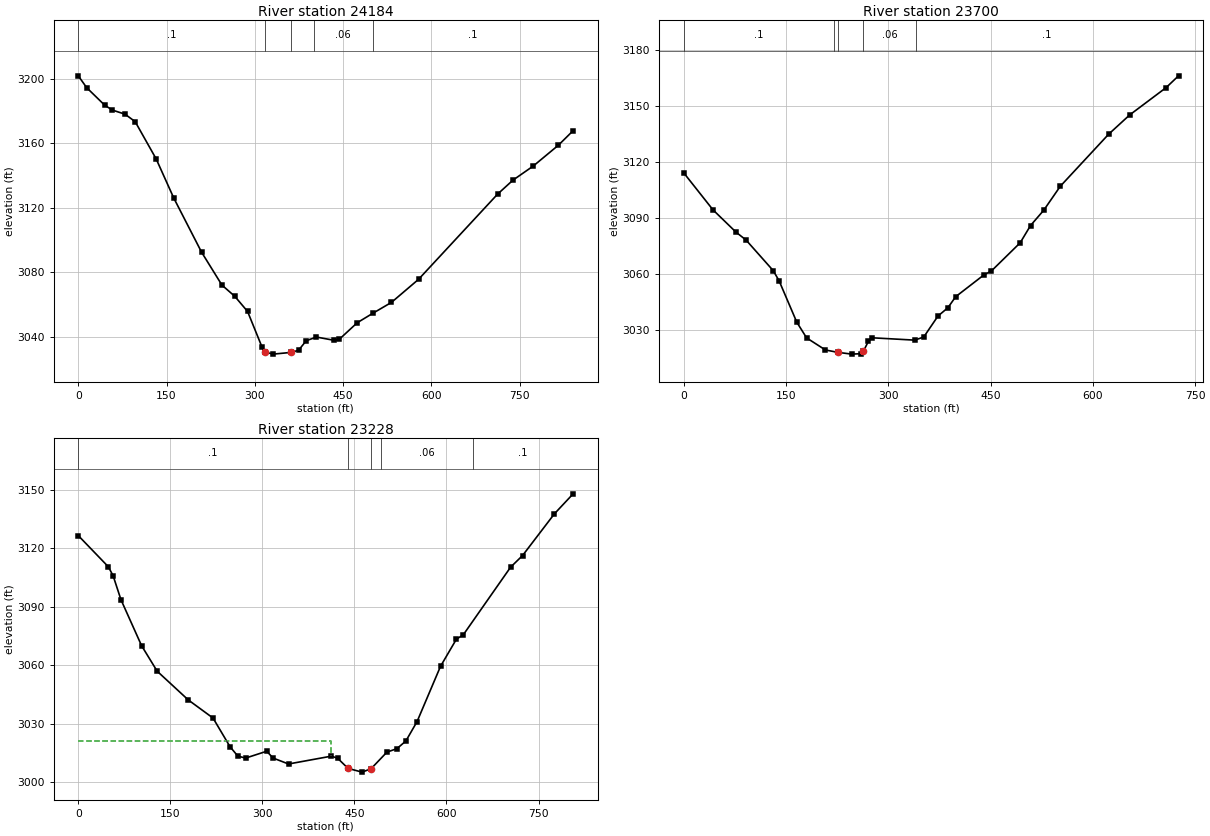
Type RM Length L Ch R = 1 ,24184   ,495.7,483.8,465.8
XS GIS Cut Line= 2
2169473.03987456477407.9882470282169797.79710791478183.391753616
#Sta/Elev= 30
       0 3201.82    14.3 3194.46    44.7 3183.66    57.7  3180.6    79.4 3178.04
    96.7 3173.37   132.4 3150.22   162.2 3126.03   209.5  3092.4   244.1    3072
   265.8 3065.09   287.6 3055.68     312  3033.7   317.9  3030.5   330.9  3029.2
     362 3030.28   374.2  3031.6   387.3 3037.52   404.6  3039.8     435 3037.74
   443.6 3038.46   473.9 3048.67     500 3054.45   532.1  3061.3   578.1  3075.6
   712.5 3128.49   738.5 3137.12   773.2 3145.93   815.8 3158.83   840.7  3167.8
#Mann= 5 ,-1,0
       0      .1       0   317.9    .045       0     362      .1       0
     400     .06       0     500      .1       0
Bank Sta=317.9,362
XS Rating Curve= 0 ,0
Exp/Cntr(USF)=0,0
Exp/Cntr=0.3,0.1

Type RM Length L Ch R = 1 ,23700   ,469.4,472.3,473.4
XS GIS Cut Line= 2
2169060.70765694477886.0017028542169659.13671614478296.509441636
#Sta/Elev= 30
       0 3114.14      43 3094.26    76.7 3082.33    91.5 3078.07   131.4 3061.65
     140 3056.18   165.9 3034.03   180.3 3025.62   207.9 3019.14   226.3 3017.87
   246.5 3016.92   260.2 3017.16   263.7 3018.57     271 3023.87   275.8 3025.69
   338.9 3024.42   352.1 3026.12     373 3037.36   387.5 3041.79   398.9  3047.7
   440.8 3059.53   451.1 3061.43   493.5 3076.61   508.7 3085.87   528.1 3094.08
   552.3  3106.9   623.3 3134.84   654.2 3145.18   707.6 3159.82   725.7 3166.11
#Mann= 5 ,-1,0
       0      .1       0     220     .06       0   226.3    .045       0
   263.7     .06       0     340      .1       0
Bank Sta=226.3,263.7
XS Rating Curve= 0 ,0
Exp/Cntr(USF)=0,0
Exp/Cntr=0.3,0.1

Type RM Length L Ch R = 1 ,23228   ,223.4,221.8,219.7
XS GIS Cut Line= 3
2168819.87645019478079.3964597912168894.68008259478300.158399314
2169339.85291931478661.405209442
#Sta/Elev= 30
       0 3126.43      49 3110.44    56.8 3105.81    69.5 3093.61   103.2 3069.97
   128.6 3056.92   179.3 3042.19   219.6 3032.92   247.4 3018.17   260.1  3013.4
   272.8 3012.42   307.1 3015.92   317.4 3012.43   342.6 3009.38   412.5  3013.4
   422.6 3012.33   439.6 3007.13   462.4 3005.21   477.1 3006.94   502.9 3015.45
   519.2 3017.23   533.8 3021.15   552.1 3031.13   590.3 3059.43   616.2 3073.36
   627.3 3075.54   704.5 3110.24     724 3116.21   775.9 3137.59   806.4 3147.83
#Mann= 5 ,-1,0
       0      .1       0   439.6    .045       0   477.1      .1       0
  493.09     .06       0  643.09      .1       0
#XS Ineff= 2 , 0
          412.54 3021.14
Permanent Ineff=
       F       F
Bank Sta=439.6,477.1
XS Rating Curve= 0 ,0
Exp/Cntr(USF)=0,0
Exp/Cntr=0.3,0.1