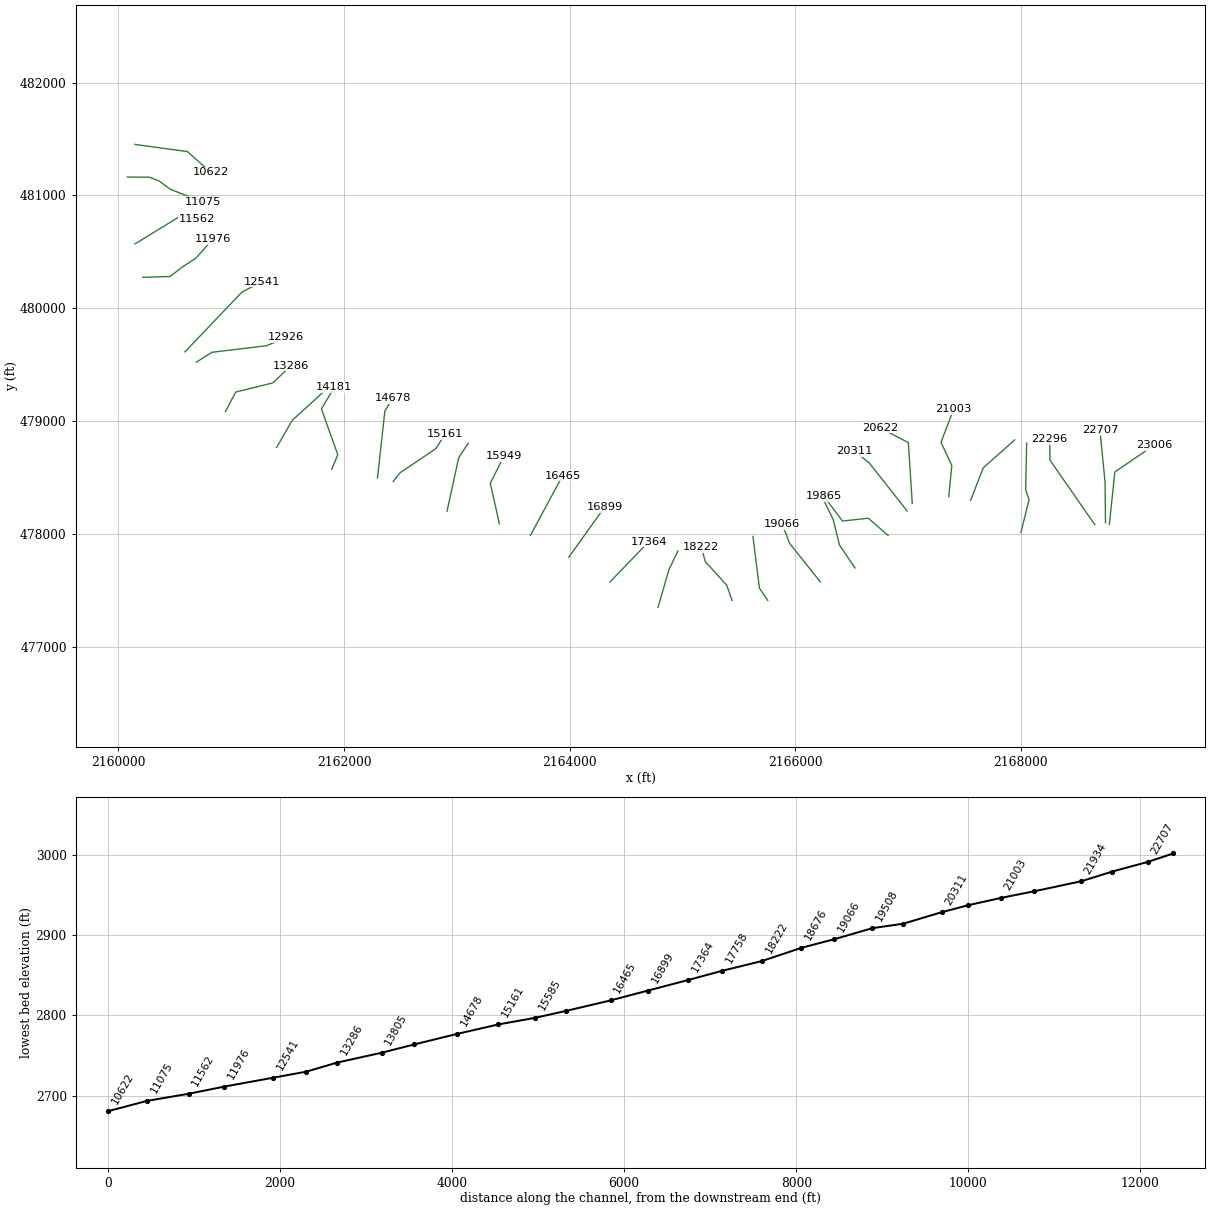
HEC-RAS study MFWILLIAMSRV.prj: MFWILLIAMSRV

--- MFWILLIAMSRV.g01 (geometry) --- (continued)

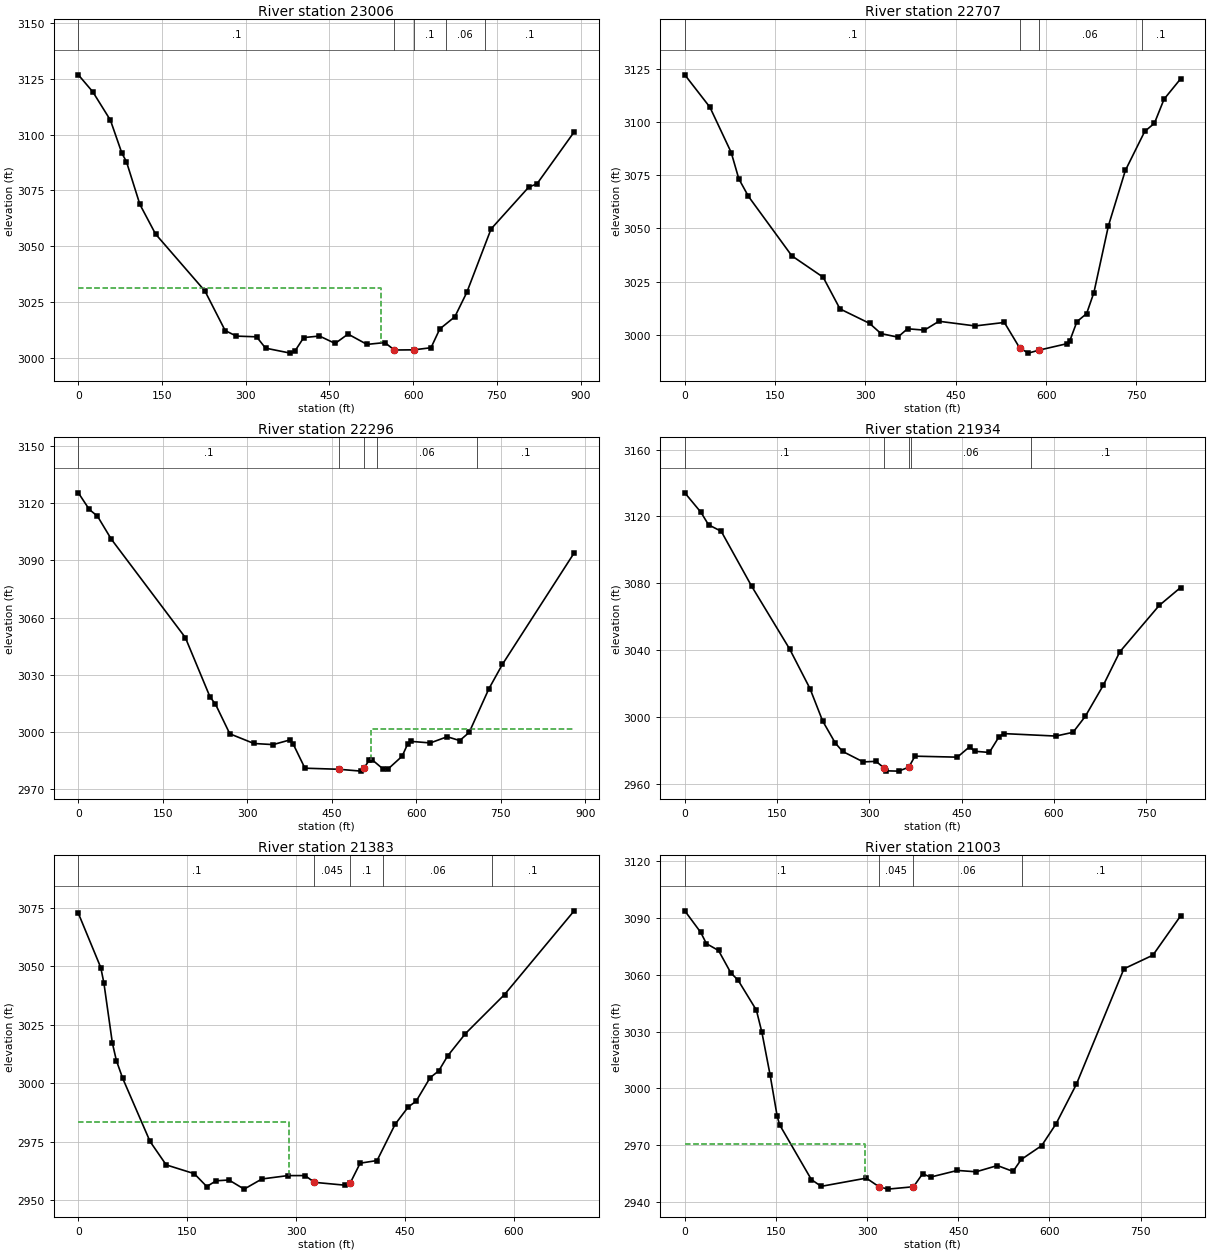
Type RM Length L Ch R = 1 ,23006   ,266.1,298.3,310.2
XS GIS Cut Line= 3
2168786.69705806478083.4930274622168835.71394038478549.153409526
2169183.28819685478785.325660717
#Sta/Elev= 30
       0 3126.74    25.8 3119.17    57.5 3106.44    78.1 3091.61    86.2 3087.88
   110.3 3068.73   138.4 3055.47   226.9 3029.96   263.1 3012.27   283.2 3009.79
   319.4 3009.47   335.5  3004.4   379.8 3002.17   387.8 3002.97   403.9 3009.13
   432.1 3009.82   460.2  3006.5   483.3  3010.7   517.2 3006.08   549.2 3006.89
   566.43003.565   601.53003.646     632 3004.59   647.7 3012.99   674.7 3018.44
   696.1 3029.34   739.6 3057.75   807.3 3076.53   821.8 3077.91   888.5 3101.17
#Mann= 5 ,-1,0
       0      .1       0   566.4    .045       0   601.5      .1       0
  658.23     .06       0  728.23      .1       0
#XS Ineff= 2 , 0
          542.03 3031.36
Permanent Ineff=
       F       F
Bank Sta=566.4,601.5
XS Rating Curve= 0 ,0
Exp/Cntr(USF)=0,0
Exp/Cntr=0.3,0.1

Type RM Length L Ch R = 1 ,22707   ,397.5,411.4,421
XS GIS Cut Line= 3
2168752.37073314478099.4657270212168748.61297937478457.819983167
2168703.10980449478920.481204584
#Sta/Elev= 30
       0 3122.04    41.7 3106.86    77.1  3085.6    89.7 3073.27   105.7 3065.04
   177.7 3037.18   229.7 3027.16   257.7 3012.29   306.7 3005.53   325.7 3000.74
   353.7 2999.05   369.8 3002.98   397.9 3002.34     422  3006.5     482 3004.31
   530.6 3005.94   556.12993.971   570.4 2991.56   587.42992.906   635.1 2996.02
   639.1 2997.18   651.1 3006.32   667.2 3010.09   679.3 3019.97   703.4 3051.24
   731.5 3077.19   763.7 3095.51   779.8 3099.34   795.8 3110.64   823.3 3120.17
#Mann= 4 ,-1,0
       0      .1       0   556.1    .045       0   587.4     .06       0
  758.37      .1       0
Bank Sta=556.1,587.4
XS Rating Curve= 0 ,0
Exp/Cntr(USF)=0,0
Exp/Cntr=0.3,0.1

Type RM Length L Ch R = 1 ,22296   ,367.3,361.7,353.1
XS GIS Cut Line= 3
2168657.49783352 478081.220938632168259.76144661478654.107294086
2168257.93696777478836.555177989
#Sta/Elev= 30
       0  3125.4    19.4 3116.71      34 3113.15    58.4 3101.16   189.9 3049.55
   233.7 3018.44   243.4 3014.64   268.8 2999.13   311.6 2994.05   345.7 2993.47
   374.9 2995.87   381.1 2993.89   402.1 2981.11   462.6 2980.54   501.5 2979.57
   506.4 2980.96   516.1 2985.22     521 2985.62   540.5 2980.76   550.2 2980.84
   574.6 2987.37   584.3  2993.7   590.1 2995.17   624.6 2994.34   654.6 2997.59
   676.8 2995.58   693.6 2999.86   728.5 3022.68   752.5 3035.48   879.9 3093.91
#Mann= 5 ,-1,0
       0      .1       0   462.6    .045       0   506.4      .1       0
     530     .06       0  707.42      .1       0
#XS Ineff= 1 ,-1
  518.72879.8759 3001.65
Permanent Ineff=
       F
Bank Sta=462.6,506.4
XS Rating Curve= 0 ,0
Exp/Cntr(USF)=0,0
Exp/Cntr=0.3,0.1

Type RM Length L Ch R = 1 ,21934   ,573.7,551,519
XS GIS Cut Line= 4
 2168002.5359731478011.7622830292168074.61590863478300.776409349
2168044.73161727478390.7365342032168053.72379752478804.099938039
#Sta/Elev= 30
       0 3134.18    26.2 3122.53    38.6 3115.02    59.2 3111.14   108.6 3078.28
   170.5 3040.56   203.5 3016.91   224.1 2997.48   244.7 2984.22   256.6 2979.24
     290 2972.96   310.9 2973.28   323.6 2969.45   327.8  2967.6   347.6 2967.43
   364.1 2969.77   374.2 2976.39   443.1  2975.8   463.1 2982.05   471.1 2979.34
   495.1 2978.62   511.1 2988.17   519.1 2989.91   603.2 2988.44   631.2 2990.69
   651.2  3000.3   680.4  3018.9   707.2  3038.9   771.2 3066.67   806.1 3077.45
#Mann= 5 ,-1,0
       0      .1       0   323.6    .045       0   364.1      .1       0
  367.87     .06       0  562.66      .1       0
Bank Sta=323.6,364.1
XS Rating Curve= 0 ,0
Exp/Cntr(USF)=0,0
Exp/Cntr=0.3,0.1

Type RM Length L Ch R = 1 ,21383   ,326.6,380,407.7
XS GIS Cut Line= 3
2167556.28512728478296.3549391272167668.98191056478585.351395534
2167947.77556513 478832.90622031
#Sta/Elev= 30
       0 3072.66    30.9 3049.47    35.2 3042.91    46.9 3017.21    52.4 3009.78
      61 3002.25    98.8  2975.2     121 2965.21   159.7 2961.45   176.9 2955.96
   189.8 2958.41   207.5 2958.74   228.4 2954.85   252.9 2959.19   288.5 2960.62
   312.3 2960.64   325.2 2957.75     368 2956.51   374.7 2957.56   388.2 2965.93
   411.5 2967.06   436.4 2982.55   454.5 2989.95   465.3 2992.39   484.6 3002.45
   496.5 3005.37   508.7 3011.72   533.3 3021.29   587.1 3037.95     683  3073.7
#Mann= 5 ,-1,0
       0      .1       0   325.2    .045       0   374.7      .1       0
  420.19     .06       0  570.19      .1       0
#XS Ineff= 2 , 0
          290.57 2983.37
Permanent Ineff=
       F       F
Bank Sta=325.2,374.7
XS Rating Curve= 0 ,0
Exp/Cntr(USF)=0,0
Exp/Cntr=0.3,0.1

Type RM Length L Ch R = 1 ,21003   ,386.8,381.1,365.4
XS GIS Cut Line= 4
2167362.70982505  478329.88994242167389.87041955 478605.18141324
2167294.04621631478811.8335638942167405.62238771479102.698211842
#Sta/Elev= 30
       0 3093.89    26.3 3082.46    35.5 3076.55    55.5 3072.91    75.7  3061.1
    87.7 3057.19   117.8 3041.35   126.9 3029.57   140.3 3007.21     152 2985.27
     156 2980.74   208.3 2951.74   224.4 2948.16   298.7 2952.51   319.32948.007
   333.9 2946.69   376.32947.943   391.3  2954.8   404.5 2953.06   448.6 2956.58
   479.4 2955.86   514.4 2959.16   540.1 2956.05   553.6 2962.37   587.3 2969.71
   610.9 2981.23   644.4 3002.18   722.6 3063.22   770.3 3070.44   815.9 3091.23
#Mann= 4 ,-1,0
       0      .1       0   319.3    .045       0   376.3     .06       0
  554.42      .1       0
#XS Ineff= 2 , 0
          296.62 2970.44
Permanent Ineff=
       F       F
Bank Sta=319.3,376.3
XS Rating Curve= 0 ,0
Exp/Cntr(USF)=0,0
Exp/Cntr=0.3,0.1

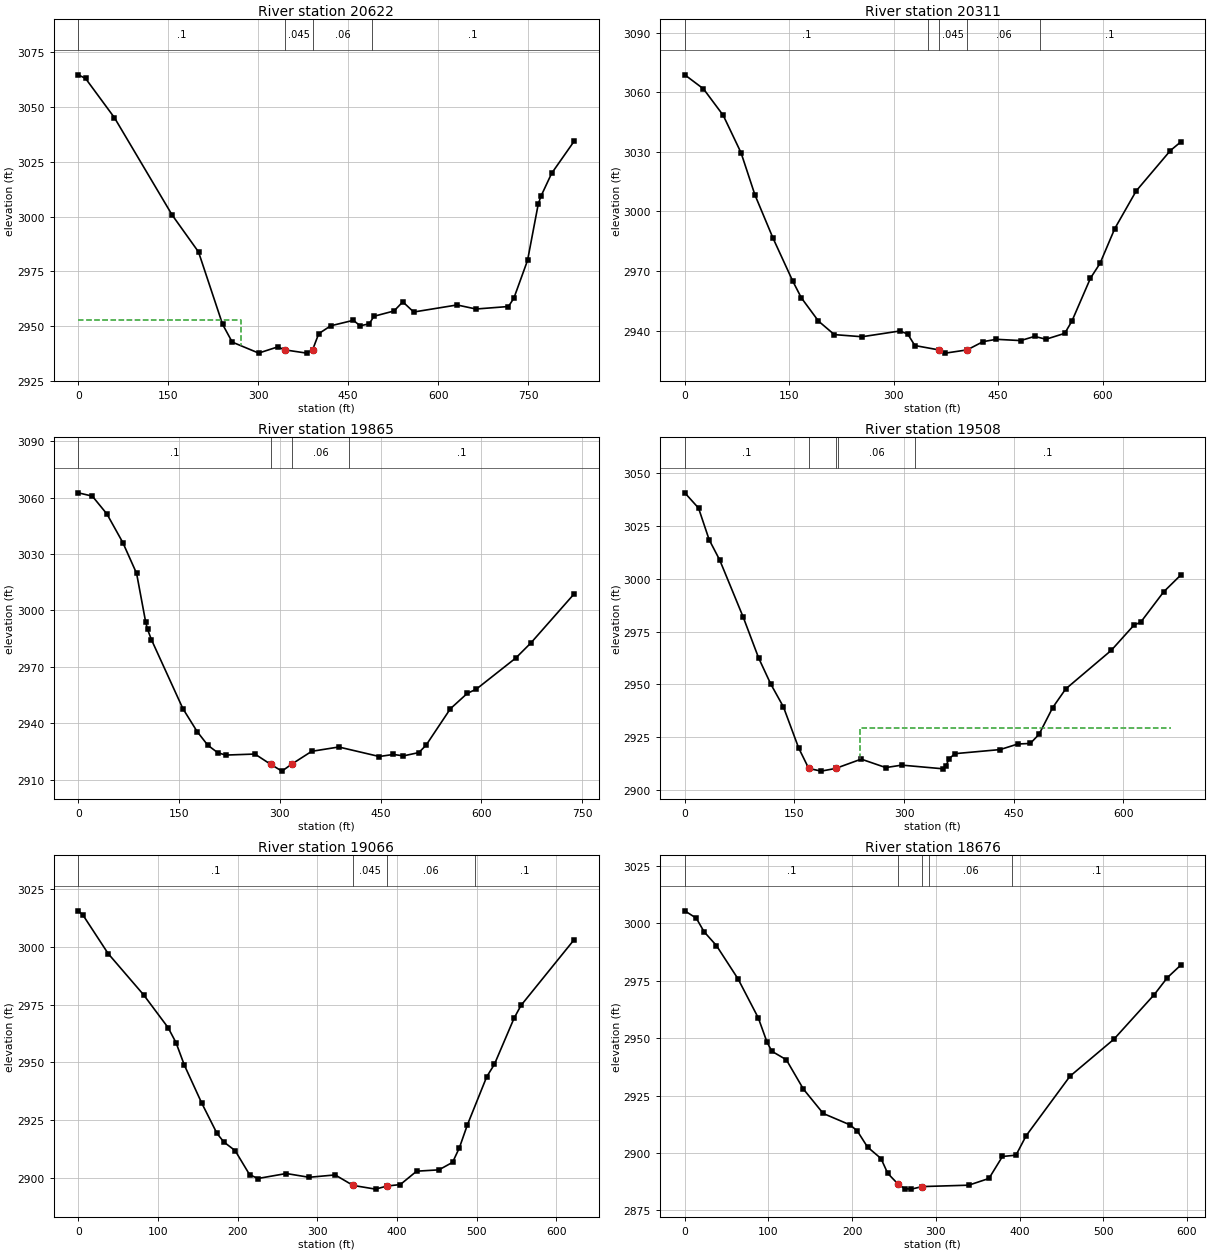
Type RM Length L Ch R = 1 ,20622   ,283.8,311.7,320.4
XS GIS Cut Line= 3
 2167039.1851033478269.1422590512167004.52000535478809.187995403
2166750.91744673478940.550471813
#Sta/Elev= 30
       0 3064.72    12.1 3063.05    60.2 3045.14   156.4  3000.7   200.4 2983.83
   240.5 2950.78   256.6 2942.64   300.7 2937.62   332.7 2940.46   343.8 2939.11
   380.8  2937.6   390.8 2939.22   400.9  2946.5   420.9 2950.08   458.6 2952.59
   469.9 2950.09     485 2950.97     493 2954.44   526.4 2956.85   541.1 2961.03
   559.2 2956.38   631.6  2959.6   663.1 2957.75   717.2 2958.89   726.2 2962.65
   749.1 2979.98   766.9 3005.67   771.3 3009.18   789.3 3019.75   826.8  3034.4
#Mann= 4 ,-1,0
       0      .1       0   343.8    .045       0   390.8     .06       0
     490      .1       0
#XS Ineff= 2 , 0
          270.67 2952.94
Permanent Ineff=
       F       F
Bank Sta=343.8,390.8
XS Rating Curve= 0 ,0
Exp/Cntr(USF)=0,0
Exp/Cntr=0.3,0.1

Type RM Length L Ch R = 1 ,20311   ,416.2,445.5,462.4
XS GIS Cut Line= 3
2166994.31960208478201.7146703792166657.86902594478628.564590339
2166526.50654953478734.384363003
#Sta/Elev= 30
       0 3068.72    26.8 3061.67    55.2 3048.33    80.8 3029.52   100.8 3008.28
   126.6 2986.68   154.9 2965.11   167.4 2956.57     192 2944.88   214.8 2938.08
   254.6 2937.01   308.8 2939.89   320.2 2938.38   330.4 2932.59   365.3 2930.37
   374.3 2928.77   405.6  2930.4   428.4 2934.54   447.5 2935.72   482.5 2935.08
   502.4 2937.18   518.8 2935.76   545.7 2938.71     556 2944.83   582.7 2966.46
   596.4 2973.88   617.6 2991.39   648.4 3010.34   697.5 3030.64   712.2 3034.91
#Mann= 5 ,-1,0
       0      .1       0     350     .06       0   365.3    .045       0
   405.6     .06       0     510      .1       0
Bank Sta=365.3,405.6
XS Rating Curve= 0 ,0
Exp/Cntr(USF)=0,0
Exp/Cntr=0.3,0.1

Type RM Length L Ch R = 1 ,19865   ,379.6,357.1,332.8
XS GIS Cut Line= 4
2166825.63894064  477985.27302332166649.37754945478138.320795568
 2166420.2799943 478113.268377152166256.07689879 478332.67820662
#Sta/Elev= 30
       0 3062.58    20.8 3060.82    42.6 3051.29    66.2 3036.11    86.7 3019.71
   100.2 2993.83     103 2989.93   108.7  2984.5   155.6 2947.74   176.8 2935.53
   192.6 2928.29   207.3 2924.31   219.1 2923.01   262.8 2923.56   286.3 2918.08
     303 2914.47   317.5 2918.17   347.3 2925.01   387.6 2927.31   447.9 2922.25
   468.8 2923.34   483.9 2922.59   506.8 2924.35   517.5 2928.26   553.7 2947.67
   578.7  2955.8   592.5 2958.16     651 2974.66   673.6 2982.72   737.9 3008.81
#Mann= 4 ,-1,0
       0      .1       0   286.3    .045       0   317.5     .06       0
  403.43      .1       0
Bank Sta=286.3,317.5
XS Rating Curve= 0 ,0
Exp/Cntr(USF)=0,0
Exp/Cntr=0.3,0.1

Type RM Length L Ch R = 1 ,19508   ,435.2,441.6,443.1
XS GIS Cut Line= 4
2166531.76838442477697.6632741942166393.84689439477900.295352055
2166337.52209937478128.3420831062166250.26554893478306.279479224
#Sta/Elev= 30
       0 3040.65    18.8 3033.43    33.3 3018.46    47.8 3008.81      80 2981.73
     101 2962.49   117.4 2950.28   134.9 2939.34   155.7 2919.93   169.52910.221
   186.5 2908.94   206.2  2910.2   241.3 2914.62   274.9 2910.62   296.8 2911.78
   353.2 2910.04   357.3  2911.4   361.4 2914.79   369.6 2917.21   431.4 2919.14
   455.4 2921.77   472.6 2922.04   484.6  2926.4   503.2    2939     521 2947.83
   583.4 2966.12   614.6 2978.11   623.5 2979.37     655 2993.79   678.2 3001.67
#Mann= 5 ,-1,0
       0      .1       0   169.5    .045       0   206.2      .1       0
     210     .06       0  315.12      .1       0
#XS Ineff= 1 ,-1
  240.03   664.5 2929.32
Permanent Ineff=
       F
Bank Sta=169.5,206.2
XS Rating Curve= 0 ,0
Exp/Cntr(USF)=0,0
Exp/Cntr=0.3,0.1

Type RM Length L Ch R = 1 ,19066   ,400.4,390.1,377.9
XS GIS Cut Line= 3
2166224.54439272  477573.03312472165951.48449707477915.951585307
2165884.75125889478087.387892858
#Sta/Elev= 30
       0 3015.55     6.1 3013.56    37.4 2997.07      82  2979.2   112.7 2965.03
   122.6 2958.55   133.1  2948.8   154.7 2932.54     174 2919.32   182.5 2915.63
   196.8 2911.87   214.9  2901.5   225.3 2899.81     261 2901.97   289.6 2900.34
   322.3 2901.36   344.8 2896.83     373 2895.22   387.5 2896.57   404.1 2897.19
   424.6 2902.98   452.5 2903.55   469.7  2906.8   478.3 2913.14   488.2 2922.92
   512.6 2943.83   522.2 2949.18   546.9 2969.13   555.6 2974.66   622.3 3003.08
#Mann= 4 ,-1,0
       0      .1       0   344.8    .045       0   387.5     .06       0
  498.35      .1       0
Bank Sta=344.8,387.5
XS Rating Curve= 0 ,0
Exp/Cntr(USF)=0,0
Exp/Cntr=0.3,0.1

Type RM Length L Ch R = 1 ,18676   ,434.5,454,473
XS GIS Cut Line= 3
2165757.06767073477409.8181541552165683.91519168477518.881850195
2165626.72325352477976.417355531
#Sta/Elev= 30
       0 3005.46    13.7 3002.26    23.1 2996.32    37.8 2990.32    63.6 2975.81
    87.8 2958.82    98.2 2948.29     104 2944.28   121.3 2940.58   141.7  2927.8
   165.4 2917.17   197.6 2912.18   206.2 2909.49   218.3 2902.55   234.4 2897.55
   242.5 2891.06     255 2886.33   262.6 2884.44   270.7 2884.21   283.6 2885.32
   339.2 2885.93   363.4 2888.86   379.5 2898.43   395.7 2899.01   407.8 2907.45
   460.2  2933.4   512.6 2949.49   560.9 2968.96   576.5 2976.34   592.4 2981.75
#Mann= 5 ,-1,0
       0      .1       0     255    .045       0   283.6      .1       0
  291.32     .06       0  391.32      .1       0
Bank Sta=255,283.6
XS Rating Curve= 0 ,0
Exp/Cntr(USF)=0,0
Exp/Cntr=0.3,0.1

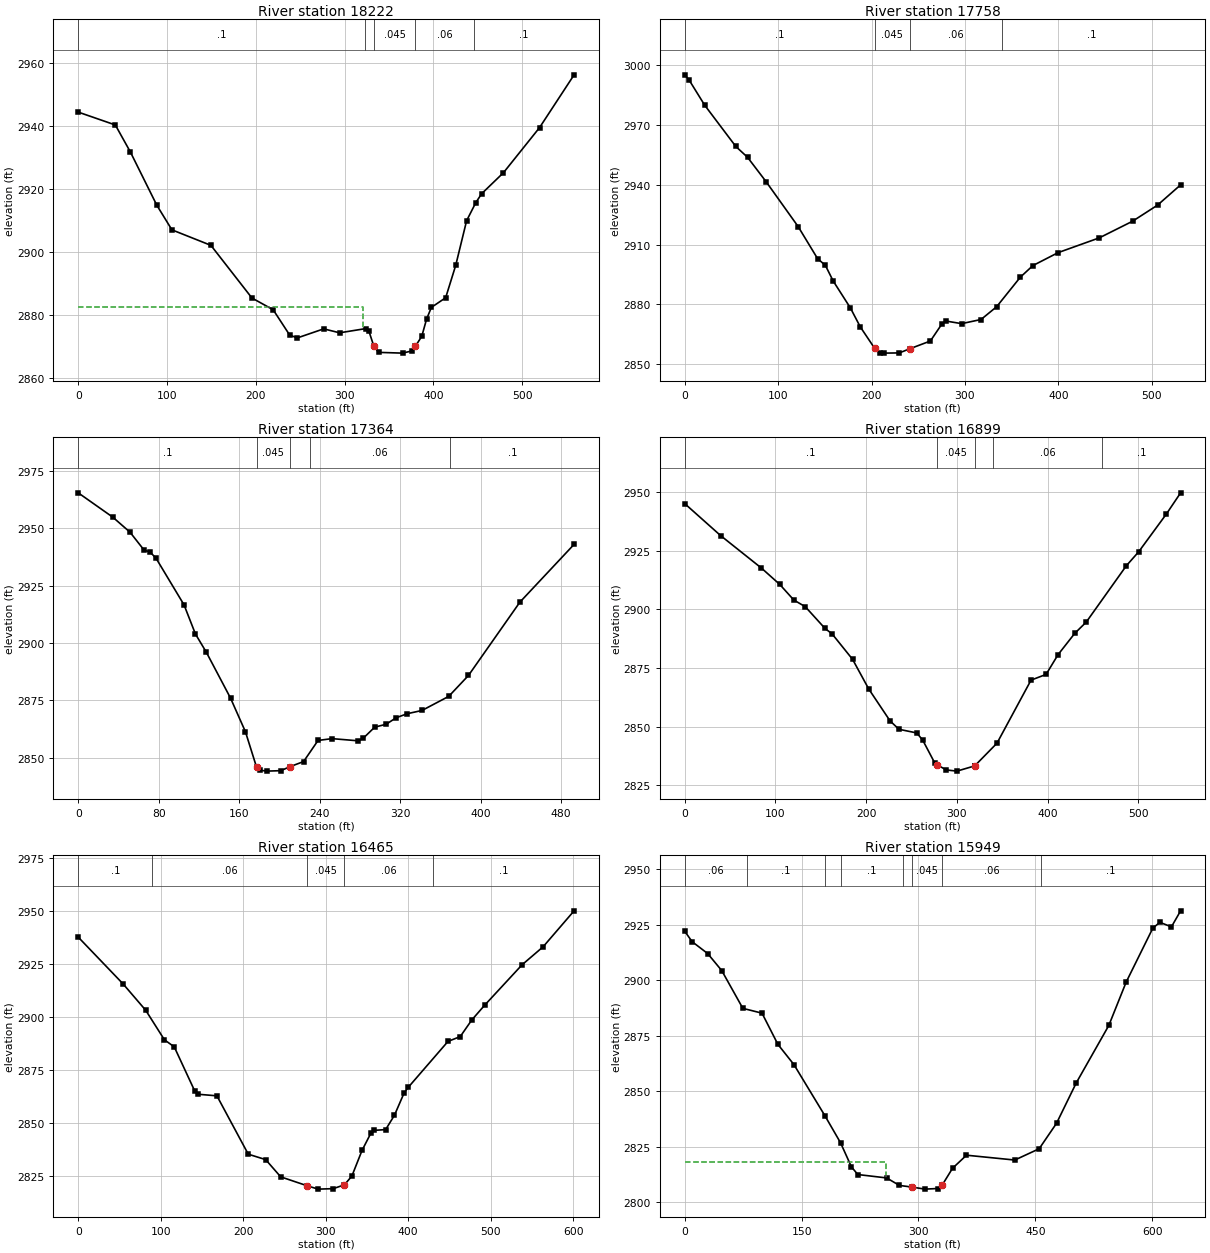
Type RM Length L Ch R = 1 ,18222   ,487.6,464,435.3
XS GIS Cut Line= 4
2165441.84698828477409.8181541552165393.96536563477544.152706594
 2165203.7689201477754.2998282312165169.18774818477881.984155302
#Sta/Elev= 30
       0 2944.35    41.8 2940.27    58.8 2931.66    88.5  2914.8   105.5 2906.99
   149.4 2902.07   195.6 2885.36   219.5 2881.63   238.1  2873.6   246.6 2872.69
   276.4 2875.57   294.3 2874.32   324.1 2875.67   327.4 2874.75   332.8 2870.11
   338.2 2868.11   365.2 2867.87     376 2868.59   379.7 2870.08   386.8 2873.21
   392.2 2878.64   397.6 2882.38   413.7 2885.45     425  2895.7   437.3  2909.9
   447.6  2915.6   454.2 2918.45   478.8 2925.13   519.4 2939.43   558.3 2956.18
#Mann= 5 ,-1,0
       0      .1       0  322.61     .06       0   332.8    .045       0
   379.7     .06       0  446.05      .1       0
#XS Ineff= 2 , 0
          320.83 2882.56
Permanent Ineff=
       F       F
Bank Sta=332.8,379.7
XS Rating Curve= 0 ,0
Exp/Cntr(USF)=0,0
Exp/Cntr=0.3,0.1

Type RM Length L Ch R = 1 ,17758   ,404.7,394.7,383.5
XS GIS Cut Line= 3
2164784.80472189477348.6360807672164883.22805734477686.467529475
2164961.70071669477847.402983387
#Sta/Elev= 30
       0 2994.89     4.7 2992.28    21.4 2979.67    54.7 2959.04    67.2 2953.66
      87  2941.5   121.4 2918.98   142.2 2902.95   150.6 2899.55   158.9 2891.77
   177.4 2878.23     188 2868.74   203.2 2858.15   208.9 2855.67   212.9 2855.66
   229.7 2855.77   240.9 2857.83     263 2861.73   275.5 2870.37   279.7 2871.71
   296.4 2870.41   317.2 2872.48   333.9 2878.86   359.3 2893.66   372.7 2899.45
   399.7 2905.93   443.9 2913.34   479.5 2921.66   506.2  2929.7   530.9 2939.84
#Mann= 4 ,-1,0
       0      .1       0   203.2    .045       0   240.9     .06       0
     340      .1       0
Bank Sta=203.2,240.9
XS Rating Curve= 0 ,0
Exp/Cntr(USF)=0,0
Exp/Cntr=0.3,0.1

Type RM Length L Ch R = 1 ,17364   ,461.2,464.8,468.6
XS GIS Cut Line= 2
2164359.19029832477573.4136982142164701.01188225 477928.53573288
#Sta/Elev= 30
       0 2965.44    34.5 2954.79    51.5 2948.28    65.6 2940.41    71.3 2939.71
    77.4 2936.91   105.2 2916.61   116.5 2903.94   127.4 2895.94   151.4 2875.99
   166.2 2861.35   177.3 2845.86   180.2 2844.62   187.2 2844.17   201.4 2844.37
   210.6 2846.13     224 2848.33   238.4 2857.54   252.3 2858.33   278.3 2857.38
   283.4 2858.53   294.7 2863.33   306.1  2864.6   316.1 2867.45   327.2 2869.21
   341.7  2870.6   368.3 2876.75   387.9 2885.85     439 2917.79   492.9 2942.98
#Mann= 5 ,-1,0
       0      .1       0   177.3    .045       0   210.6      .1       0
     230     .06       0     370      .1       0
Bank Sta=177.3,210.6
XS Rating Curve= 0 ,0
Exp/Cntr(USF)=0,0
Exp/Cntr=0.3,0.1

Type RM Length L Ch R = 1 ,16899   ,430.4,433.9,436.7
XS GIS Cut Line= 2
2163994.29371964477793.0578403682164312.02670946478237.884026112
#Sta/Elev= 30
       0 2945.12    39.5 2931.51    84.6 2917.63   104.7  2910.7   120.2 2904.05
   132.9 2901.18   154.6 2891.93   162.4 2889.62     185 2878.76   202.8 2866.14
   226.3 2852.54   236.1 2848.95   255.8 2847.39   262.4 2844.27   275.4 2834.73
   278.5 2833.76   288.2 2831.63     300 2831.12   319.7 2833.36   319.7 2833.38
   344.2 2843.04   381.7  2869.9   398.3 2872.34   411.5 2880.76   429.9 2889.83
   442.6 2894.65   486.8 2918.66   500.4 2924.61     531 2940.75   546.6 2949.72
#Mann= 5 ,-1,0
       0      .1       0   278.5    .045       0   319.7      .1       0
     340     .06       0     460      .1       0
Bank Sta=278.5,319.7
XS Rating Curve= 0 ,0
Exp/Cntr(USF)=0,0
Exp/Cntr=0.3,0.1

Type RM Length L Ch R = 1 ,16465   ,497.9,515.4,533.8
XS GIS Cut Line= 2
2163652.91548407477985.1754621182163938.13626097 478514.23783586
#Sta/Elev= 30
       0 2937.52    54.5 2915.42    81.8 2903.06   104.5 2889.14   116.4 2885.82
   141.2 2865.04   145.4 2863.49   168.1 2862.75   206.1 2835.26   227.2  2832.7
   245.4 2824.59   277.2 2820.42   290.8  2818.8     309 2819.02   322.6 2820.82
   331.7 2824.97     344 2837.05   354.5 2845.01     359 2846.49   372.6 2846.84
   383.3 2853.62   395.1 2864.21   399.9 2866.71   448.2  2888.4     463 2890.65
   477.1 2898.53   492.5 2905.39   537.9 2924.46   563.5 2932.98     601  2949.9
#Mann= 5 ,-1,0
       0      .1       0      90     .06       0   277.2    .045       0
   322.6     .06       0     430      .1       0
Bank Sta=277.2,322.6
XS Rating Curve= 0 ,0
Exp/Cntr(USF)=0,0
Exp/Cntr=0.3,0.1

Type RM Length L Ch R = 1 ,15949   ,374.2,364.8,352.4
XS GIS Cut Line= 3
2163378.66771511478088.4140987062163297.46882697478447.144286205
2163417.27936376478687.802632298
#Sta/Elev= 30
       0 2922.12     9.4 2917.43    29.4 2912.06    47.5 2904.37    74.6 2887.33
    99.2 2885.16   119.6 2871.08   140.2 2861.95     180 2838.87     200 2826.71
     214 2815.82   222.2 2812.37   259.2 2810.84   275.6 2807.46     292  2806.7
   308.4 2805.79   324.8 2806.07   330.5 2807.61   343.8  2815.2   361.7 2821.09
   423.7 2818.91     455    2824   477.3 2835.49   502.6  2853.7   544.4 2879.61
   566.7 2899.18     601 2923.56     610 2926.12   624.8 2924.09   636.6 2931.32
#Mann= 8 ,-1,0
       0     .06       0      80      .1       0     180     .06       0
     200      .1       0     280     .06       0     292    .045       0
   330.5     .06       0  457.81      .1       0
#XS Ineff= 2 , 0
          258.88 2817.96
Permanent Ineff=
       F       F
Bank Sta=292,330.5
XS Rating Curve= 0 ,0
Exp/Cntr(USF)=0,0
Exp/Cntr=0.3,0.1

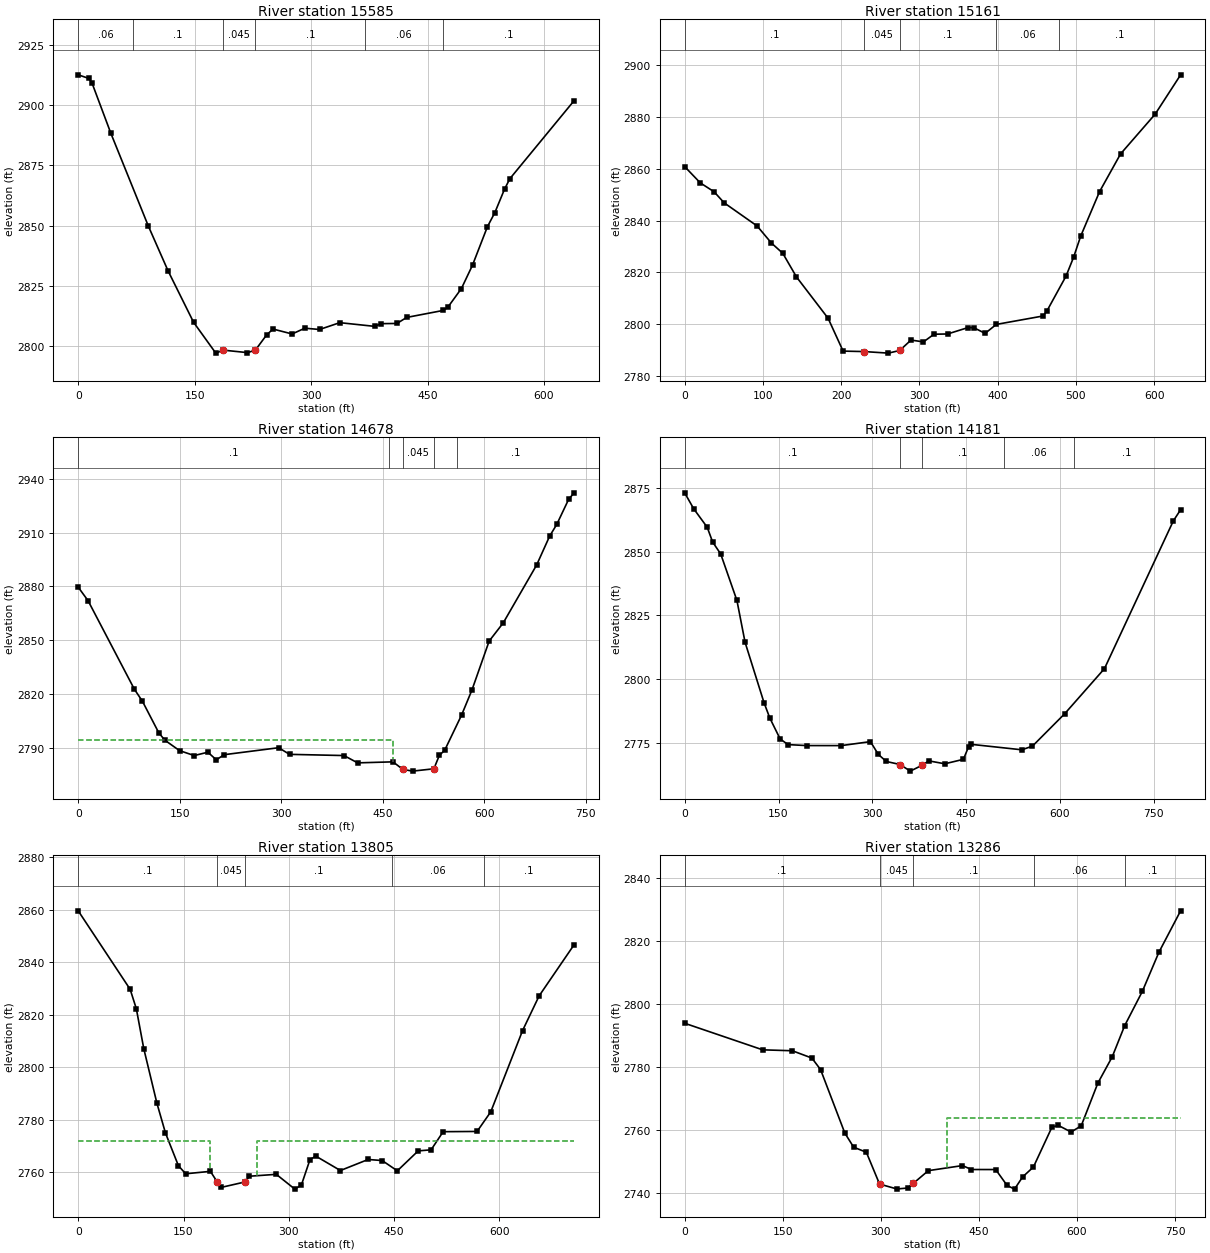
Type RM Length L Ch R = 1 ,15585   ,441.8,424.1,401.1
XS GIS Cut Line= 3
2162913.80896045478200.024534469 2163017.5524762478674.850625764
2163101.34531584478802.534952835
#Sta/Elev= 30
       0 2912.59    13.5 2911.12    17.6 2909.34    42.1 2888.26    90.3 2849.81
   115.8 2831.14   148.6 2809.83   177.2 2797.02     187 2798.26     218 2797.23
   228.1 2798.23   242.7 2804.59   250.9 2807.02   275.5 2804.98   291.9 2807.37
   310.9 2806.84   336.9 2809.67     382 2808.13   390.1 2809.26   410.6 2809.34
     423 2811.84     470 2814.74   476.1 2816.08   493.6 2823.85   507.9 2833.57
   527.1 2849.53   536.7  2855.4   549.1  2865.1     556 2869.46   638.8 2901.89
#Mann= 6 ,-1,0
       0     .06       0      70      .1       0     187    .045       0
   228.1      .1       0     370     .06       0     470      .1       0
Bank Sta=187,228.1
XS Rating Curve= 0 ,0
Exp/Cntr(USF)=0,0
Exp/Cntr=0.3,0.1

Type RM Length L Ch R = 1 ,15161   ,460.2,482.6,507.2
XS GIS Cut Line= 4
2162436.93845345 478464.422842522162497.89441917478541.831465806
2162813.85992687478754.3992694782162897.93739616 478884.10260497
#Sta/Elev= 30
       0 2860.84    19.9 2854.57    37.6 2851.12    50.5 2846.85    92.6 2837.92
   110.9 2831.33   125.4 2827.38   142.9 2818.25   183.3 2802.31   202.5 2789.63
   229.4 2789.45   260.4 2788.85   274.8 2789.87   289.3 2793.89   305.2 2793.19
   318.7 2796.15     336 2796.24   362.5 2798.74   369.7 2798.65     384 2796.47
   398.3 2799.93     458 2803.18   462.9 2805.07   487.4 2818.55     497 2825.78
   506.2 2834.02   530.3 2851.18   557.1 2865.72   601.3 2881.06   633.9 2896.26
#Mann= 5 ,-1,0
       0      .1       0   229.4    .045       0   274.8      .1       0
  398.53     .06       0  478.53      .1       0
Bank Sta=229.4,274.8
XS Rating Curve= 0 ,0
Exp/Cntr(USF)=0,0
Exp/Cntr=0.3,0.1

Type RM Length L Ch R = 1 ,14678   ,486.4,496.7,509.7
XS GIS Cut Line= 3
 2162297.3464463478494.7814989932162362.89357983 479089.49903549
2162433.67458852479203.912172815
#Sta/Elev= 30
       0  2879.6    14.5  2872.1    82.9 2822.73      95 2815.88   119.1 2798.34
     128 2794.24   149.7 2788.42   171.4 2785.66   191.6 2787.52   204.1 2783.28
   215.7 2786.14   296.2 2790.03   312.3 2786.33   392.8 2785.66   412.9 2781.58
   465.2 2782.15   479.6 2777.97   494.1 2776.97   525.6 2778.28   533.6 2785.69
   541.7 2788.71   566.6  2808.3   581.9 2822.27   607.3 2849.54   628.1 2859.68
   677.5 2892.01   696.7 2908.11   707.2 2914.63   724.9 2928.73   732.9 2932.25
#Mann= 5 ,-1,0
       0      .1       0     460     .06       0   479.6    .045       0
   525.6     .06       0     560      .1       0
#XS Ineff= 2 , 0
          464.58 2794.36
Permanent Ineff=
       F       F
Bank Sta=479.6,525.6
XS Rating Curve= 0 ,0
Exp/Cntr(USF)=0,0
Exp/Cntr=0.3,0.1

Type RM Length L Ch R = 1 ,14181   ,396.9,375.9,356.5
XS GIS Cut Line= 4
 2161891.9909573478571.8501543662161945.19276025478701.899006012
   2161800.36563479108.3016674072161914.15837519479297.463633439
#Sta/Elev= 30
       0 2873.09    14.4 2866.84      36 2859.58    44.7 2853.78    57.6 2849.08
    83.5 2830.85    96.5 2814.45   126.9 2790.67   136.1 2784.69   152.5 2776.52
   165.2 2774.27   194.9 2773.89   250.3 2773.88   296.9 2775.44   309.6  2770.4
   322.3 2767.65   344.2 2766.46   360.6 2763.86   378.7 2766.07   390.3 2767.88
   415.8 2766.74   445.5 2768.49   453.8 2773.42   458.2 2774.37   538.9 2772.23
   555.9 2773.68   607.4 2786.38     671  2804.1   781.1  2862.1   792.7 2866.46
#Mann= 5 ,-1,0
       0      .1       0   344.2    .045       0   378.7      .1       0
  510.51     .06       0  621.95      .1       0
Bank Sta=344.2,378.7
XS Rating Curve= 0 ,0
Exp/Cntr(USF)=0,0
Exp/Cntr=0.3,0.1

Type RM Length L Ch R = 1 ,13805   ,538.3,519,490.3
XS GIS Cut Line= 3
2161402.82993577478765.4456039762161541.34357366479006.160429987
2161858.49813828479294.756850851
#Sta/Elev= 30
       0  2859.5      74 2829.62    82.8 2822.23    93.4 2807.05   112.1 2786.29
   124.3 2774.95   142.8 2762.47   153.1 2759.43   188.3 2760.36   198.1 2756.29
   203.2 2754.22     2382756.343   243.9  2758.5   282.2 2759.22   308.6 2753.59
   317.9 2755.13   330.2 2764.85   338.5 2766.15   373.5 2760.67     413 2764.87
     433 2764.47   454.6 2760.56   484.3 2768.14   502.7 2768.55   519.9 2775.45
   568.2 2775.54   587.7    2783     633 2813.92   656.6 2827.13   706.5 2846.63
#Mann= 5 ,-1,0
       0      .1       0   198.1    .045       0     238      .1       0
  447.72     .06       0  577.72      .1       0
#XS Ineff= 2 , 0
          187.46  2771.8  254.74         2772.06
Permanent Ineff=
       F       F
Bank Sta=198.1,238
XS Rating Curve= 0 ,0
Exp/Cntr(USF)=0,0
Exp/Cntr=0.3,0.1

Type RM Length L Ch R = 1 ,13286   ,363.8,360.5,357
XS GIS Cut Line= 4
2160949.06567087479083.7425023642161041.03890325479257.181506499
2161368.51299116479337.968660748 2161532.4664448479491.703293422
#Sta/Elev= 30
       0 2793.96   119.3 2785.52   164.6 2785.23   194.5 2782.91   207.8 2779.25
   244.9 2759.08   258.4 2754.59   277.8 2752.99     298 2742.88   324.5 2741.32
     341 2741.62   349.82743.135   372.6 2747.14   424.8 2748.75   438.5  2747.5
   475.6 2747.49     493 2742.45   504.4 2741.27   516.8 2745.15   533.3 2748.29
   561.7 2760.99   571.5  2761.5   590.9 2759.41   606.4 2761.38   631.8 2774.93
   653.8  2783.3   672.8 2793.18   699.8 2804.06   725.2 2816.52   758.4 2829.68
#Mann= 5 ,-1,0
       0      .1       0     298    .045       0   349.8      .1       0
  533.61     .06       0  673.61      .1       0
#XS Ineff= 2 , 0
                          400.49         2763.96
Permanent Ineff=
       F       F
Bank Sta=298,349.8
XS Rating Curve= 0 ,0
Exp/Cntr(USF)=0,0
Exp/Cntr=0.3,0.1

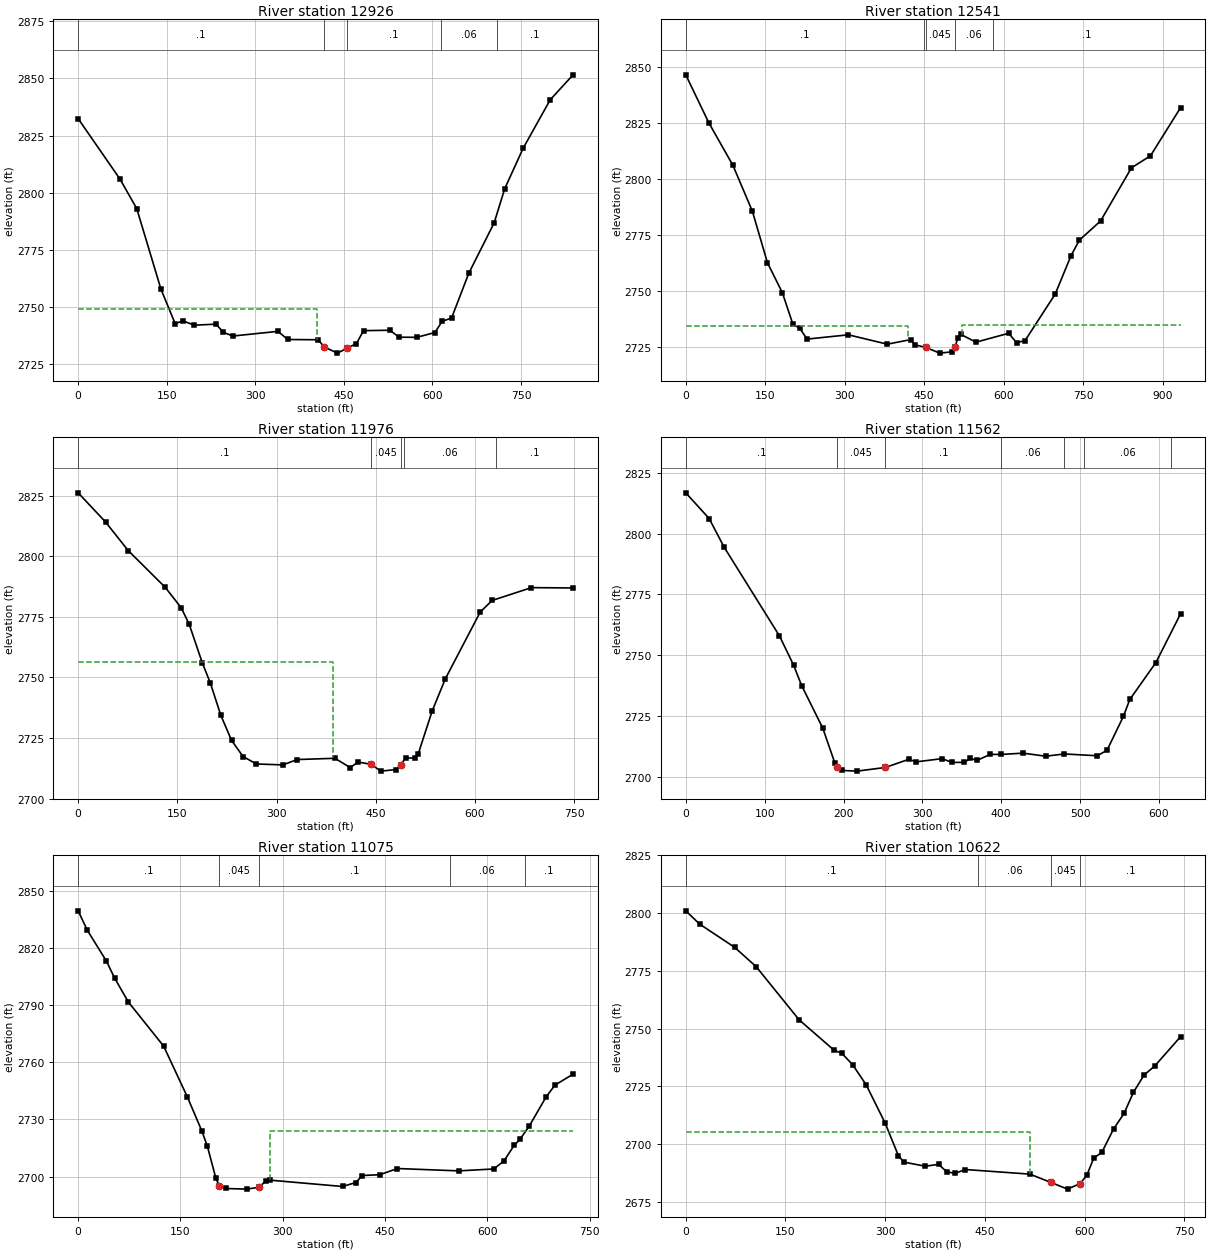
Type RM Length L Ch R = 1 ,12926   ,362.7,384.7,401.5
XS GIS Cut Line= 4
2160692.00008137479522.9955323082160831.57271256 479610.02317293
2161312.68778241479667.4942563592161486.74306365 479741.38564934
#Sta/Elev= 30
       0  2832.4    70.9 2805.94    99.2 2793.09   140.2 2757.85   164.3 2742.75
   177.2 2743.99   196.7  2742.1   233.6 2742.55   245.7 2739.02   261.8 2737.35
   338.3  2739.4     355 2735.84   406.8 2735.72   416.32732.629     439 2729.88
   455.1 2731.99   471.2 2734.05   483.3 2739.71   527.6 2739.88   543.8 2736.84
   573.3 2736.79   604.2 2738.88   616.3 2743.76   632.4 2745.25   661.5 2764.79
   704.5 2786.86   722.3 2801.73   753.6 2819.47   799.4 2840.64   838.1 2851.56
#Mann= 5 ,-1,0
       0      .1       0   416.3    .045       0   455.1      .1       0
  614.48     .06       0  709.02      .1       0
#XS Ineff= 2 , 0
          404.76 2749.07
Permanent Ineff=
       F       F
Bank Sta=416.3,455.1
XS Rating Curve= 0 ,0
Exp/Cntr(USF)=0,0
Exp/Cntr=0.3,0.1

Type RM Length L Ch R = 1 ,12541   ,570.9,564.7,555.7
XS GIS Cut Line= 3
2160590.19416215 479613.307234842161097.58172729480145.325264303
2161274.92107044480235.636966835
#Sta/Elev= 30
       0 2846.32    43.4 2824.99      89 2806.01   125.8 2785.51   154.1 2762.67
   182.4 2749.22   202.2 2735.24   215.4 2733.36   228.9 2728.61   306.9 2730.52
   380.4 2726.35   425.4 2728.43   431.8  2726.1   453.1 2724.91   479.4 2722.36
   502.8 2722.94   508.3 2725.12   513.4  2729.1   519.4 2730.68   547.7 2727.24
   609.6  2731.2   624.4 2727.03   640.4 2727.94   697.3 2748.62   727.3 2765.81
   742.9 2772.67     783 2781.22   841.3 2804.91   877.2 2810.25   934.2 2831.74
#Mann= 5 ,-1,0
       0      .1       0     450     .06       0   453.1    .045       0
   508.3     .06       0     580      .1       0
#XS Ineff= 2 ,-1
       0  419.53 2734.49  521.52934.1882 2734.87
Permanent Ineff=
       F       F
Bank Sta=453.1,508.3
XS Rating Curve= 0 ,0
Exp/Cntr(USF)=0,0
Exp/Cntr=0.3,0.1

Type RM Length L Ch R = 1 ,11976   ,412.9,414.3,406.2
XS GIS Cut Line= 5
2160216.47730986480274.2710792232160457.77314012480281.709406179
2160578.07068677480372.9911101152160686.97699413480444.085127882
2160837.96534635480612.322655611
#Sta/Elev= 30
       0 2826.16    41.4 2814.13    75.7 2802.33   131.8 2787.13   155.8 2778.75
   167.8 2772.03   187.8 2755.96   199.8 2747.78   215.8 2734.33     232 2723.99
   249.4 2717.35   269.5 2714.27   309.7 2713.89   331.2  2716.1   388.3 2716.62
   411.4  2712.8   423.6 2715.07   443.2 2714.12   457.7 2711.32   480.8 2711.97
   487.9 2713.98   495.2 2716.69   509.6 2716.78   514.4  2718.5   535.4 2736.12
   555.3 2749.39   608.1 2776.97   626.1 2781.75   685.6 2787.04   748.5  2786.9
#Mann= 5 ,-1,0
       0      .1       0   443.2    .045       0   487.9      .1       0
  492.42     .06       0  632.48      .1       0
#XS Ineff= 2 , 0
          384.93 2756.52
Permanent Ineff=
       F       F
Bank Sta=443.2,487.9
XS Rating Curve= 0 ,0
Exp/Cntr(USF)=0,0
Exp/Cntr=0.3,0.1

Type RM Length L Ch R = 1 ,11562   ,508.9,486.9,445.1
XS GIS Cut Line= 3
2160146.84580427480570.6112816822160560.63760496480823.484048772
2160698.56820519480787.359367759
#Sta/Elev= 30
       0 2816.78    29.7 2806.19    48.4 2794.56   118.8 2757.95   136.7 2745.94
   146.9 2737.54   173.7 2720.04   189.1 2705.61     192 2704.02   198.4 2702.64
   217.2 2702.36   253.1 2703.87   282.8 2707.22   292.2 2706.18     325 2707.49
   337.4 2705.96   353.1 2705.96   360.7 2707.57   369.5 2706.79     386 2709.25
     400 2709.23   427.6 2709.75   456.3 2708.49     480 2709.42   521.7 2708.68
   534.1 2710.92   554.8 2724.82     563 2731.82   596.1 2747.01   627.5 2767.14
#Mann= 7 ,-1,0
       0      .1       0     192    .045       0   253.1      .1       0
     400     .06       0     480      .1       0  504.94     .06       0
  614.94      .1       0
Bank Sta=192,253.1
XS Rating Curve= 0 ,0
Exp/Cntr(USF)=0,0
Exp/Cntr=0.3,0.1

Type RM Length L Ch R = 1 ,11075   ,473.5,452.9,443
XS GIS Cut Line= 5
2160078.73689141481163.9373518232160274.30190931481162.128992052
 2160359.8185326481129.348656154 2160462.0988103481053.681102261
2160752.93603187480943.154757514
#Sta/Elev= 30
       0 2839.42    13.4 2829.24    41.4 2813.08    53.4 2804.18    73.4  2791.7
   125.4 2768.41   160.2  2741.7   181.4 2723.89   189.4 2715.96   201.9 2699.12
   207.12695.037   216.3 2693.79   247.3 2693.46   265.22694.456   274.7 2697.63
   281.4 2698.16   387.6 2694.84     407 2696.92   416.6 2700.59   442.3 2701.03
     468 2704.27   557.8 2703.03   609.2 2704.03   624.2 2708.23   639.1 2716.38
   647.7 2719.58   661.3 2726.52   686.1 2741.89     699 2748.01   725.5 2753.76
#Mann= 5 ,-1,0
       0      .1       0   207.1    .045       0   265.2      .1       0
  544.38     .06       0  654.38      .1       0
#XS Ineff= 2 , 0
                          280.57         2723.74
Permanent Ineff=
       F       F
Bank Sta=207.1,265.2
XS Rating Curve= 0 ,0
Exp/Cntr(USF)=0,0
Exp/Cntr=0.3,0.1

Type RM Length L Ch R = 1 ,10622   ,457.7,487.9,513.8
XS GIS Cut Line= 3
2160147.31889305 481452.717568152160612.90435475481389.343000867
2160817.20403324481205.869958804
#Sta/Elev= 30
       0 2800.94      21 2795.17    73.5 2785.16   105.8 2776.82   170.4 2753.84
   222.9  2740.7     235 2739.24   251.2 2734.32   271.3 2725.72   299.6 2709.34
   319.8 2695.11   327.9 2692.28   360.1 2690.49   380.3 2691.28   392.4 2688.14
   404.6 2687.38   420.7 2689.06   517.6 2687.07   548.7 2683.54   574.3 2680.58
   593.42683.012   603.3 2686.59   613.9 2694.06   625.8 2696.44   643.7 2706.66
   659.3  2713.3   673.4 2722.43   689.3 2729.88   705.5 2733.84   744.5 2746.56
#Mann= 4 ,-1,0
       0      .1       0     440     .06       0   548.7    .045       0
   593.4      .1       0
#XS Ineff= 2 , 0
          517.41 2705.48
Permanent Ineff=
       F       F
Bank Sta=548.7,593.4
XS Rating Curve= 0 ,0
Exp/Cntr(USF)=0,0
Exp/Cntr=0.3,0.1