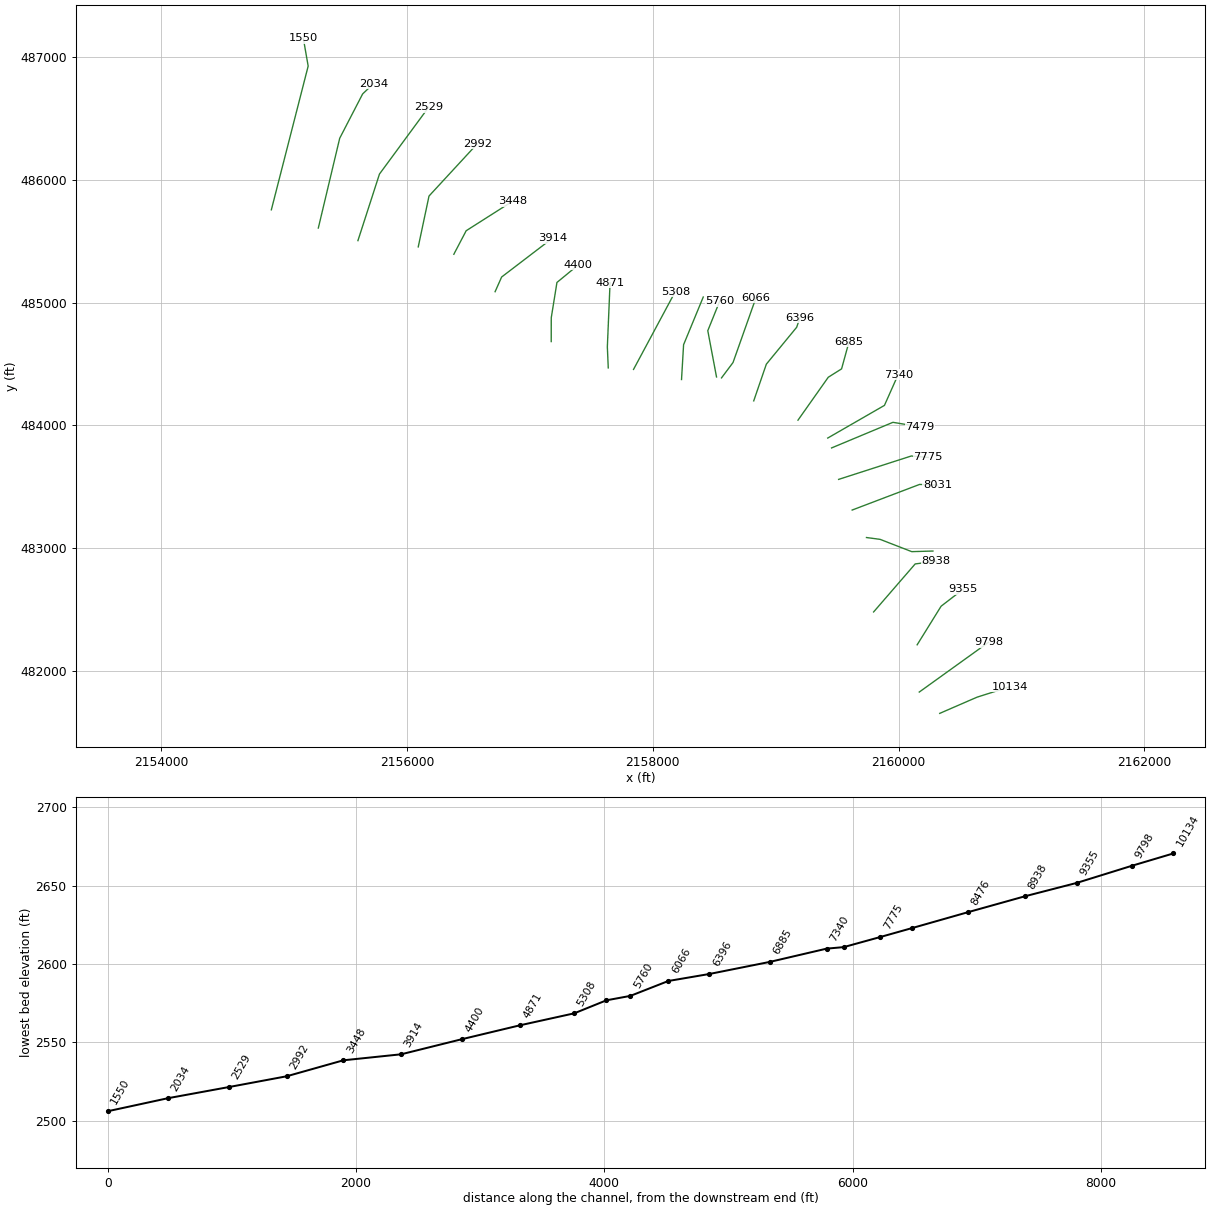
HEC-RAS study MFWILLIAMSRV.prj: MFWILLIAMSRV

--- MFWILLIAMSRV.g01 (geometry) --- (continued)

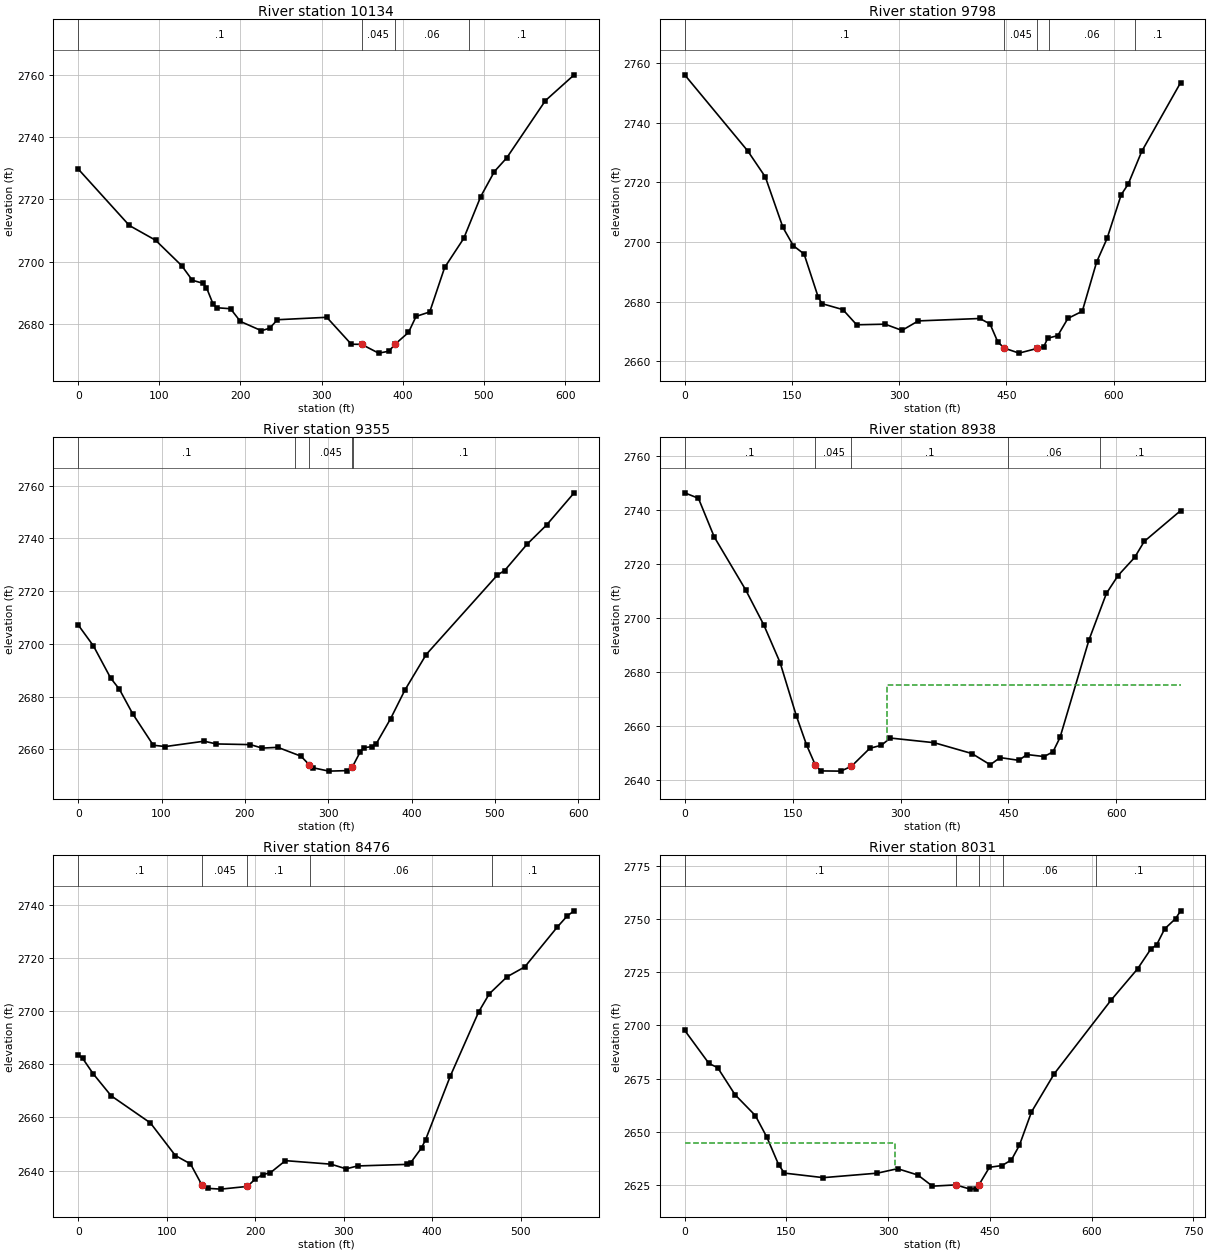
Type RM Length L Ch R = 1 ,10134   ,324.4,336.1,342.6
XS GIS Cut Line= 3
2160335.20844885481655.2104849442160638.83010003481787.098754632
2160905.86670654 481871.96978989
#Sta/Elev= 30
       0 2729.77      63 2711.63    95.3  2706.9   127.5 2698.73   140.6 2694.04
   153.7 2693.06   158.1 2691.64   166.4 2686.27   171.1  2685.2   187.7 2684.88
   199.9  2680.8   225.8 2677.82   235.9 2678.62   245.5 2681.35   306.3 2682.13
   336.6 2673.47   349.2 2673.45   370.2 2670.62   382.8 2671.22   390.7 2673.53
     407 2677.26   416.4 2682.42   433.2 2683.85   451.6 2698.14   475.1 2707.47
   496.1 2720.94   512.9 2728.96     528 2733.32   575.8 2751.75   611.2 2760.03
#Mann= 4 ,-1,0
       0      .1       0   349.2    .045       0   390.7     .06       0
  481.03      .1       0
Bank Sta=349.2,390.7
XS Rating Curve= 0 ,0
Exp/Cntr(USF)=0,0
Exp/Cntr=0.3,0.1

Type RM Length L Ch R = 1 ,9798    ,428.4,443.6,453.2
XS GIS Cut Line= 2
2160168.62347355481828.7366470432160731.67588806482233.661480578
#Sta/Elev= 30
       0 2756.06    88.1 2730.55   112.8 2721.79   137.4 2704.86   151.9 2698.74
     167 2695.93   186.7 2681.49     192 2679.29   221.2 2677.29   240.5  2672.2
   280.3  2672.4   303.8 2670.32   326.7  2673.5   412.7 2674.31     427 2672.47
   437.9 2666.41   447.1 2664.36   467.5 2662.69   492.9 2664.27     502 2664.81
   507.7 2667.68   521.7 2668.57   535.9 2674.34     556 2676.74     576 2693.22
   590.7  2701.2   610.4 2715.83   620.2 2719.39   639.1 2730.36   693.5 2753.45
#Mann= 5 ,-1,0
       0      .1       0   447.1    .045       0   492.9      .1       0
     510     .06       0     630      .1       0
Bank Sta=447.1,492.9
XS Rating Curve= 0 ,0
Exp/Cntr(USF)=0,0
Exp/Cntr=0.3,0.1

Type RM Length L Ch R = 1 ,9355    ,421.4,416.9,412.4
XS GIS Cut Line= 3
2160151.69333402482213.596735953 2160346.5762987482527.913227736
2160524.96956739482665.345156615
#Sta/Elev= 30
       0 2707.19    18.3 2699.23    38.9 2687.07    49.4 2682.82    65.4 2673.49
    90.1 2661.58   104.6 2661.09   151.1 2663.12   165.6 2662.08   206.6 2661.82
   220.7  2660.5   239.5 2660.79   267.3 2657.43   277.12654.194   281.8 2653.04
   300.7 2651.77   322.5 2651.96     329  2653.4   338.4 2659.11   342.5 2660.65
   352.5 2661.06   357.7 2662.24   374.7  2671.6     392 2682.54   417.5 2695.99
     503 2726.15   511.6 2727.82   538.5  2737.8     562 2745.12     595 2757.29
#Mann= 5 ,-1,0
       0      .1       0     260     .06       0   277.1    .045       0
     329     .06       0     330      .1       0
Bank Sta=277.1,329
XS Rating Curve= 0 ,0
Exp/Cntr(USF)=0,0
Exp/Cntr=0.3,0.1

Type RM Length L Ch R = 1 ,8938    ,501.9,462.1,427.8
XS GIS Cut Line= 3
2159797.24725201482481.1271330842160135.50562876482871.930500406
 2160306.2768481482894.918933778
#Sta/Elev= 30
       0 2746.33    19.1 2744.31    41.1 2729.98    84.7 2710.41   109.9 2697.43
   132.6 2683.44   155.2  2663.7   169.5 2652.85   181.7 2645.41   189.3 2643.32
     217 2643.24   231.8 2645.04   257.3  2651.7   273.4 2652.83   285.7  2655.5
   346.7 2653.77   399.1 2649.76   424.6  2645.6   438.4 2648.25   464.3 2647.24
   475.7 2649.38   499.5 2648.64   511.8 2650.38   521.6  2655.7   561.9 2691.87
   586.1 2709.09   602.3  2715.7   625.3 2722.39   638.6 2728.32   689.2 2739.73
#Mann= 5 ,-1,0
       0      .1       0   181.7    .045       0   231.8      .1       0
     450     .06       0  576.86      .1       0
#XS Ineff= 1 ,-1
  280.83689.1733 2674.96
Permanent Ineff=
       F
Bank Sta=181.7,231.8
XS Rating Curve= 0 ,0
Exp/Cntr(USF)=0,0
Exp/Cntr=0.3,0.1

Type RM Length L Ch R = 1 ,8476    ,423.7,444.6,457.3
XS GIS Cut Line= 4
2159739.32283667483087.0365555292159849.79224257483072.258276932
2160107.59110253482972.0943886692160280.00435282482977.020481535
#Sta/Elev= 30
       0  2683.6     4.9 2682.32      17 2676.44    37.2 2668.18    81.6 2657.94
   109.8 2645.66   126.9 2642.51   139.8 2634.55   146.6  2633.3   161.2 2633.01
   191.3 2634.03   199.8 2636.75   208.4  2638.5     217 2639.14   234.2 2643.74
   285.7 2642.41   302.8 2640.65   315.7 2641.74   371.5 2642.33   375.8 2642.98
     388 2648.55   392.6 2651.65   420.6 2675.65   452.6 2699.79   464.6 2706.59
   484.7 2713.02   504.7 2716.73   541.4 2731.73   552.7 2735.94   560.5 2737.86
#Mann= 5 ,-1,0
       0      .1       0   139.8    .045       0   191.3      .1       0
  261.45     .06       0  468.03      .1       0
Bank Sta=139.8,191.3
XS Rating Curve= 0 ,0
Exp/Cntr(USF)=0,0
Exp/Cntr=0.3,0.1

Type RM Length L Ch R = 1 ,8031    ,257.6,256.6,254.4
XS GIS Cut Line= 3
2159622.75861994483310.8618436762160171.19695895483519.399774978
2160315.69568301483514.473682112
#Sta/Elev= 30
       0 2697.69    35.8  2682.1    48.6 2680.14    74.3 2667.38   104.2  2657.6
   121.3 2647.35   138.5 2634.51     147 2630.53   204.4 2628.39     284  2630.5
   313.9  2632.6   343.9 2629.62   365.3 2624.39   399.8 2624.98   420.9 2622.99
   429.5  2623.2   433.5  2624.8   449.4 2633.26     468 2634.09   481.8 2636.73
   493.6 2643.63   511.4 2659.31     545 2677.28   628.5 2711.81   667.8  2726.6
   687.8 2736.12   695.8 2737.82   707.8 2745.42   723.8  2750.2   731.3  2753.9
#Mann= 5 ,-1,0
       0      .1       0   399.8    .045       0   433.5      .1       0
     470     .06       0  606.75      .1       0
#XS Ineff= 2 , 0
          309.68 2644.49
Permanent Ineff=
       F       F
Bank Sta=399.8,433.5
XS Rating Curve= 0 ,0
Exp/Cntr(USF)=0,0
Exp/Cntr=0.3,0.1

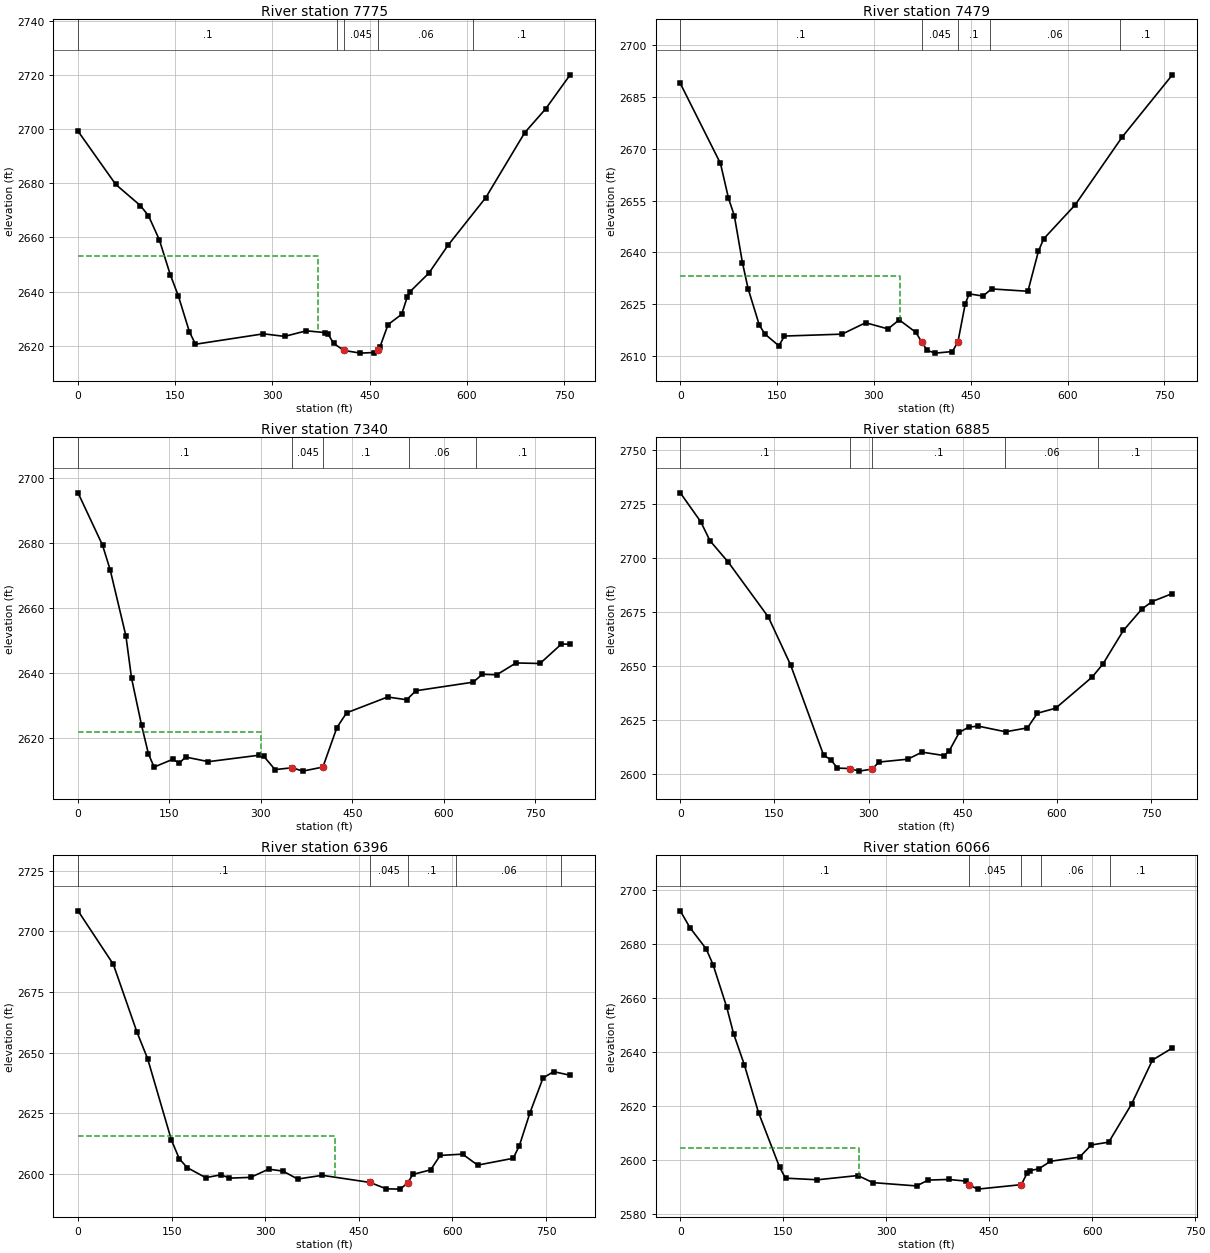
Type RM Length L Ch R = 1 ,7775    ,293,296,298.5
XS GIS Cut Line= 3
2159512.74254595483560.4505488562160103.87368979483750.926139652
2160241.80429003483739.431922966
#Sta/Elev= 30
       0 2699.24    58.2 2679.57    96.1 2671.79   108.7 2668.03   125.5 2659.13
   142.3 2646.29   154.9 2638.36   171.9 2625.14   181.3 2620.56   286.2  2624.4
   318.8 2623.45   352.4 2625.51   381.8 2624.84     386 2624.28   394.4 2620.89
   410.1 2618.29   435.6 2617.27   457.5  2617.5     463 2618.54   465.9  2619.5
   478.5 2627.81   499.5  2631.6   507.9 2637.85   512.1 2639.89   541.5 2646.82
   570.9 2657.06   629.4 2674.73   689.5 2698.72   721.7 2707.47   759.5 2720.05
#Mann= 5 ,-1,0
       0      .1       0     400     .06       0   410.1    .045       0
     463     .06       0     610      .1       0
#XS Ineff= 2 , 0
          371.07 2653.18
Permanent Ineff=
       F       F
Bank Sta=410.1,463
XS Rating Curve= 0 ,0
Exp/Cntr(USF)=0,0
Exp/Cntr=0.3,0.1

Type RM Length L Ch R = 1 ,7479    ,133.3,138.1,142
XS GIS Cut Line= 3
2159455.27146252483816.6073778572159954.44887288484025.145309159
2160172.83898991483989.020628146
#Sta/Elev= 30
       0 2688.99    62.3 2665.76    74.7 2655.68    83.7 2650.65    96.3 2637.02
     105 2629.52   122.4 2618.94     131 2616.33   152.7 2612.92   161.4 2615.74
   250.5 2616.29   287.1  2619.6   321.8 2617.81   339.1 2620.43   364.7 2616.85
   374.2 2613.98   382.5 2611.57   395.2 2610.79   421.5 2611.25   430.1 2614.05
   441.4 2625.04   447.5 2627.97   468.9 2627.33   482.2  2629.4   538.5 2628.72
   554.9 2640.39     563 2643.93   611.7 2653.76   684.6 2673.45   762.3 2691.46
#Mann= 5 ,-1,0
       0      .1       0   374.2    .045       0   430.1      .1       0
     480     .06       0  680.99      .1       0
#XS Ineff= 2 , 0
          340.35 2633.09
Permanent Ineff=
       F       F
Bank Sta=374.2,430.1
XS Rating Curve= 0 ,0
Exp/Cntr(USF)=0,0
Exp/Cntr=0.3,0.1

Type RM Length L Ch R = 1 ,7340    ,436,455.5,464.1
XS GIS Cut Line= 3
2159424.07287437483897.0668946582159885.48357276 484163.07590939
2159997.14167771484414.306645526
#Sta/Elev= 30
       0 2695.37    40.3 2679.24    52.9 2671.59    78.6 2651.36    87.8 2638.42
   104.3 2623.87   115.5 2615.15   124.8 2611.06   155.4 2613.44   166.3 2612.27
   176.4 2614.15     214 2612.72   296.5 2614.69   304.8 2614.36   323.3 2610.28
   351.6 2610.85   368.6 2609.81   401.8 2611.06   424.8 2623.21   440.7 2627.73
     508  2632.6   539.3 2631.75   554.4 2634.52   648.4 2637.16   663.5 2639.59
     687 2639.42   718.7 2643.07   758.1  2642.9   793.2 2648.88   807.5 2648.84
#Mann= 5 ,-1,0
       0      .1       0   351.6    .045       0   401.8      .1       0
   542.6     .06       0   652.6      .1       0
#XS Ineff= 2 , 0
          301.05 2621.86
Permanent Ineff=
       F       F
Bank Sta=351.6,401.8
XS Rating Curve= 0 ,0
Exp/Cntr(USF)=0,0
Exp/Cntr=0.3,0.1

Type RM Length L Ch R = 1 ,6885    ,486,488.8,489
XS GIS Cut Line= 4
2159181.86788135484042.5593511882159428.52242035484392.322811682
2159536.68251209484460.4236101872159597.11222659 484680.43261879
#Sta/Elev= 30
       0 2730.07    32.6 2716.71    47.3 2707.93    76.6 2697.96   140.3 2672.64
   175.8 2650.47   228.4 2608.72     240 2606.62   250.3 2602.78   270.2 2602.58
   284.8 2601.38   305.72602.328   316.5 2605.57   362.3  2606.9   385.3 2610.16
   420.4 2608.57   428.4 2610.72   444.6 2619.32   459.6 2621.74   474.6 2622.19
   518.3 2619.57   553.1 2621.38     569 2628.16   598.1 2630.48   656.1 2644.85
   673.2 2650.84   705.9 2666.41     735  2676.2   751.5 2679.77     784  2683.5
#Mann= 5 ,-1,0
       0      .1       0   270.2    .045       0   305.7      .1       0
  517.99     .06       0   665.8      .1       0
Bank Sta=270.2,305.7
XS Rating Curve= 0 ,0
Exp/Cntr(USF)=0,0
Exp/Cntr=0.3,0.1

Type RM Length L Ch R = 1 ,6396    ,318.1,330.4,344.5
XS GIS Cut Line= 4
 2158821.8226964484199.6288225772158924.36048472484498.579778581
 2159171.1414613484798.9246380462159198.48398554484878.168544134
#Sta/Elev= 30
       0 2708.49    56.6  2686.4    94.4 2658.46   111.6 2647.42   149.6 2613.92
   162.3 2606.14     175  2602.5   204.7 2598.35   229.2 2599.56   242.7 2598.17
   276.5 2598.48   305.4 2601.87   328.4 2601.08   351.9 2597.79   391.4 2599.33
   467.82596.396     494 2593.75   516.1 2593.63   528.1 2596.14   536.6  2599.7
     565 2601.58   580.4 2607.54   616.2 2608.07   640.4 2603.54   697.3 2606.35
   707.2 2611.52   724.1 2625.06   745.2 2639.52   762.2 2642.12   788.6 2640.62
#Mann= 5 ,-1,0
       0      .1       0   467.8    .045       0   528.1      .1       0
  606.05     .06       0  774.77      .1       0
#XS Ineff= 2 , 0
          412.57 2615.62
Permanent Ineff=
       F       F
Bank Sta=467.8,528.1
XS Rating Curve= 0 ,0
Exp/Cntr(USF)=0,0
Exp/Cntr=0.3,0.1

Type RM Length L Ch R = 1 ,6066    ,293.3,305.7,339.4
XS GIS Cut Line= 3
 2158559.7482939484387.0186475892158653.34405834 484511.81300018
2158840.53558723485040.546967733
#Sta/Elev= 30
       0 2692.16      14 2685.96    37.7 2678.09    47.7 2672.29    67.6 2656.56
    77.7 2646.66    93.3 2635.21     114 2617.47   144.7 2597.26   153.3 2593.22
   199.9 2592.62   258.7 2594.19   280.5 2591.57   344.2 2590.34   361.1 2592.51
   390.8 2592.74   416.3 2592.13   420.5 2590.72   433.3 2589.16   496.9 2590.82
   505.4 2595.17   509.6 2596.03   522.4 2596.67   539.3 2599.46   581.8 2601.03
   598.7  2605.5   624.2 2606.54   657.6 2620.71   687.9 2636.94   716.9  2641.4
#Mann= 5 ,-1,0
       0      .1       0   420.5    .045       0   496.9      .1       0
  525.99     .06       0  625.99      .1       0
#XS Ineff= 2 , 0
          259.65  2604.3
Permanent Ineff=
       F       F
Bank Sta=420.5,496.9
XS Rating Curve= 0 ,0
Exp/Cntr(USF)=0,0
Exp/Cntr=0.3,0.1

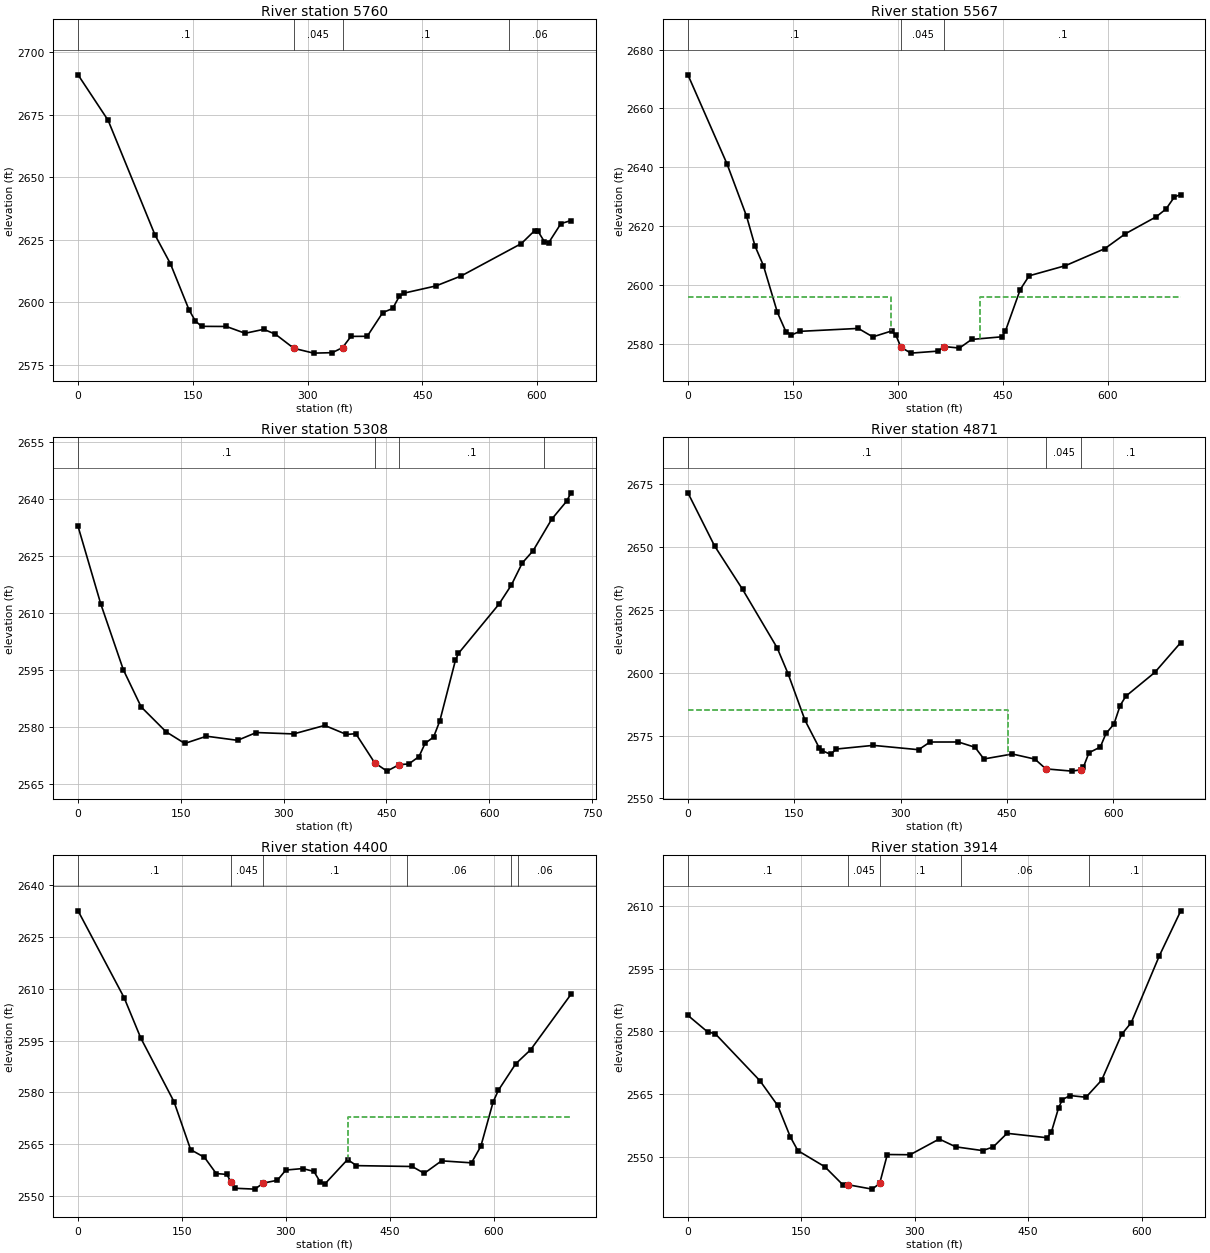
Type RM Length L Ch R = 1 ,5760    ,218.3,193.2,177.8
XS GIS Cut Line= 3
2158519.07672097484394.5982248562158448.07162371484771.188964035
2158545.78291646485013.291753751
#Sta/Elev= 30
       0 2690.86    39.3 2672.67   100.6 2626.86   120.7 2615.41   145.1 2596.93
   153.2 2592.54   161.4 2590.35   193.9  2590.3   218.4 2587.58   242.8 2589.16
   258.1 2587.19   282.1 2581.57   307.9 2579.65   332.3 2579.83   345.7 2581.84
   356.8 2586.34     378 2586.37   398.3 2595.84   411.3  2597.5   419.9 2602.31
   426.3 2603.64   467.8  2606.5   501.1 2610.53   579.5 2623.43   596.7 2628.55
     601 2628.47   609.7 2624.16   615.3 2623.81   631.2 2631.39   644.3 2632.63
#Mann= 4 ,-1,0
       0      .1       0   282.1    .045       0   345.7      .1       0
  563.23     .06       0
Bank Sta=282.1,345.7
XS Rating Curve= 0 ,0
Exp/Cntr(USF)=0,0
Exp/Cntr=0.3,0.1

Type RM Length L Ch R = 1 ,5567    ,266.9,259.2,256.2
XS GIS Cut Line= 3
2158234.37585986484373.4629775722158251.18019744484657.131254122
2158411.23363883 485045.56238074
#Sta/Elev= 30
       0 2671.41    55.8 2641.18    83.9 2623.29    95.9 2613.21   107.9 2606.57
   127.9 2590.63     140 2584.13     148 2582.99     160 2584.22   243.5 2585.22
   264.2 2582.34   291.1 2584.35   297.3 2582.84   304.5 2578.79   318.7 2576.82
   357.8 2577.51   366.4 2579.05     388 2578.54   405.4 2581.47   448.6 2582.37
   453.5 2584.18   474.9 2598.43   487.6  2603.1   539.5 2606.55   595.7 2612.32
     625 2617.37   669.3 2623.17   683.3 2625.83   695.2  2629.9   704.3 2630.72
#Mann= 3 ,-1,0
       0      .1       0   304.5    .045       0   366.4      .1       0
#XS Ineff= 2 , 0
          289.97 2595.79   417.3         2595.79
Permanent Ineff=
       F       F
Bank Sta=304.5,366.4
XS Rating Curve= 0 ,0
Exp/Cntr(USF)=0,0
Exp/Cntr=0.3,0.1

Type RM Length L Ch R = 1 ,5308    ,424.3,437.1,449.4
XS GIS Cut Line= 2
2157843.82279746484455.9839477052158183.72320517485089.807896387
#Sta/Elev= 30
       0 2632.86    33.1  2612.5    66.1 2595.15    92.1 2585.39   128.4 2578.86
   155.7 2575.79   187.4 2577.69   232.8 2576.61   260.1 2578.66   314.5 2578.29
   359.9 2580.53   391.7 2578.15   405.3 2578.36   432.7 2570.73   450.7 2568.51
   468.9 2570.24   482.5 2570.38   497.5 2572.33   506.4 2575.81   518.8 2577.47
   527.9 2581.72   550.7 2597.67   555.1 2599.47   614.1 2612.39   632.3 2617.44
   648.2 2623.24     664 2626.46   691.3 2634.79   713.2 2639.54   719.2 2641.69
#Mann= 4 ,-1,0
       0      .1       0   432.7    .045       0   468.9      .1       0
     680     .06       0
Bank Sta=432.7,468.9
XS Rating Curve= 0 ,0
Exp/Cntr(USF)=0,0
Exp/Cntr=0.3,0.1

Type RM Length L Ch R = 1 ,4871    ,475.4,470.8,469.6
XS GIS Cut Line= 3
2157638.21632063484468.0292537722157630.82718133484639.457285488
2157652.99459922485162.608347794
#Sta/Elev= 30
       0 2671.41    37.6 2650.32    77.2 2633.02   125.9 2609.83   141.3 2599.54
   165.3 2580.98   185.3 2570.06   189.3 2569.01   201.3 2567.53   209.3 2569.64
   261.4  2571.1   325.4 2569.38   341.5 2572.43   381.5 2572.44     405 2570.34
   417.5  2565.7   457.6 2567.67   489.5 2565.64   504.8 2561.77   541.6 2560.87
   554.8 2561.42   557.7 2562.34   565.7 2568.18   581.7 2570.43   589.7 2575.82
   600.9 2579.53   609.7 2586.93   617.7 2590.63   658.5 2600.06   695.2 2611.95
#Mann= 3 ,-1,0
       0      .1       0   504.8    .045       0   554.8      .1       0
#XS Ineff= 2 , 0
          451.73 2585.21
Permanent Ineff=
       F       F
Bank Sta=504.8,554.8
XS Rating Curve= 0 ,0
Exp/Cntr(USF)=0,0
Exp/Cntr=0.3,0.1

Type RM Length L Ch R = 1 ,4400    ,510.4,485.9,467.8
XS GIS Cut Line= 4
2157174.18183206484682.6442651252157174.51180377484876.903117503
2157220.66522028485163.9720924382157395.48748194485307.765449745
#Sta/Elev= 30
       0 2632.61    66.5 2607.43    90.5 2595.75   138.5 2577.28   162.5 2563.38
   182.5 2561.14   199.4 2556.46   214.8  2556.2   220.4 2554.11   226.9 2552.19
   255.1 2551.94   267.5 2553.69   287.7 2554.51   299.9 2557.47   324.2  2557.9
   340.4 2557.08   349.5 2554.01   356.6 2553.51     389 2560.52   401.9 2558.75
   482.2  2558.5   499.7 2556.52   524.7 2560.14   567.9 2559.56   581.4 2564.37
   599.2 2577.26   606.6 2580.56   631.7 2588.26   653.2 2592.33   711.4 2608.38
#Mann= 6 ,-1,0
       0      .1       0   220.4    .045       0   267.5      .1       0
  474.26     .06       0  625.01      .1       0  635.01     .06       0
#XS Ineff= 2 , 0
                          389.13         2572.77
Permanent Ineff=
       F       F
Bank Sta=220.4,267.5
XS Rating Curve= 0 ,0
Exp/Cntr(USF)=0,0
Exp/Cntr=0.3,0.1

Type RM Length L Ch R = 1 ,3914    ,468.6,465.8,463
XS GIS Cut Line= 3
2156717.52956408485088.7169548132156770.73136703485208.421011442
2157184.52316772485524.676173401
#Sta/Elev= 30
       0 2583.83    26.2 2579.86    36.1 2579.46    95.2 2568.24   118.7 2562.33
   135.4 2554.84   145.4 2551.55   181.1  2547.7   204.7 2543.43   211.3 2543.42
   243.6 2542.36   253.6 2543.71   263.7 2550.62   293.9 2550.57   332.3 2554.32
   354.3 2552.45   389.6 2551.56   403.7 2552.42   422.1 2555.68   475.2 2554.62
   480.7 2556.01   490.3 2561.82   495.3 2563.74   505.4  2564.7   526.4 2564.29
   547.2 2568.38   573.6 2579.29   586.3 2582.11   623.4 2598.03   651.8 2608.79
#Mann= 5 ,-1,0
       0      .1       0   211.3    .045       0   253.6      .1       0
  360.99     .06       0  530.99      .1       0
Bank Sta=211.3,253.6
XS Rating Curve= 0 ,0
Exp/Cntr(USF)=0,0
Exp/Cntr=0.3,0.1

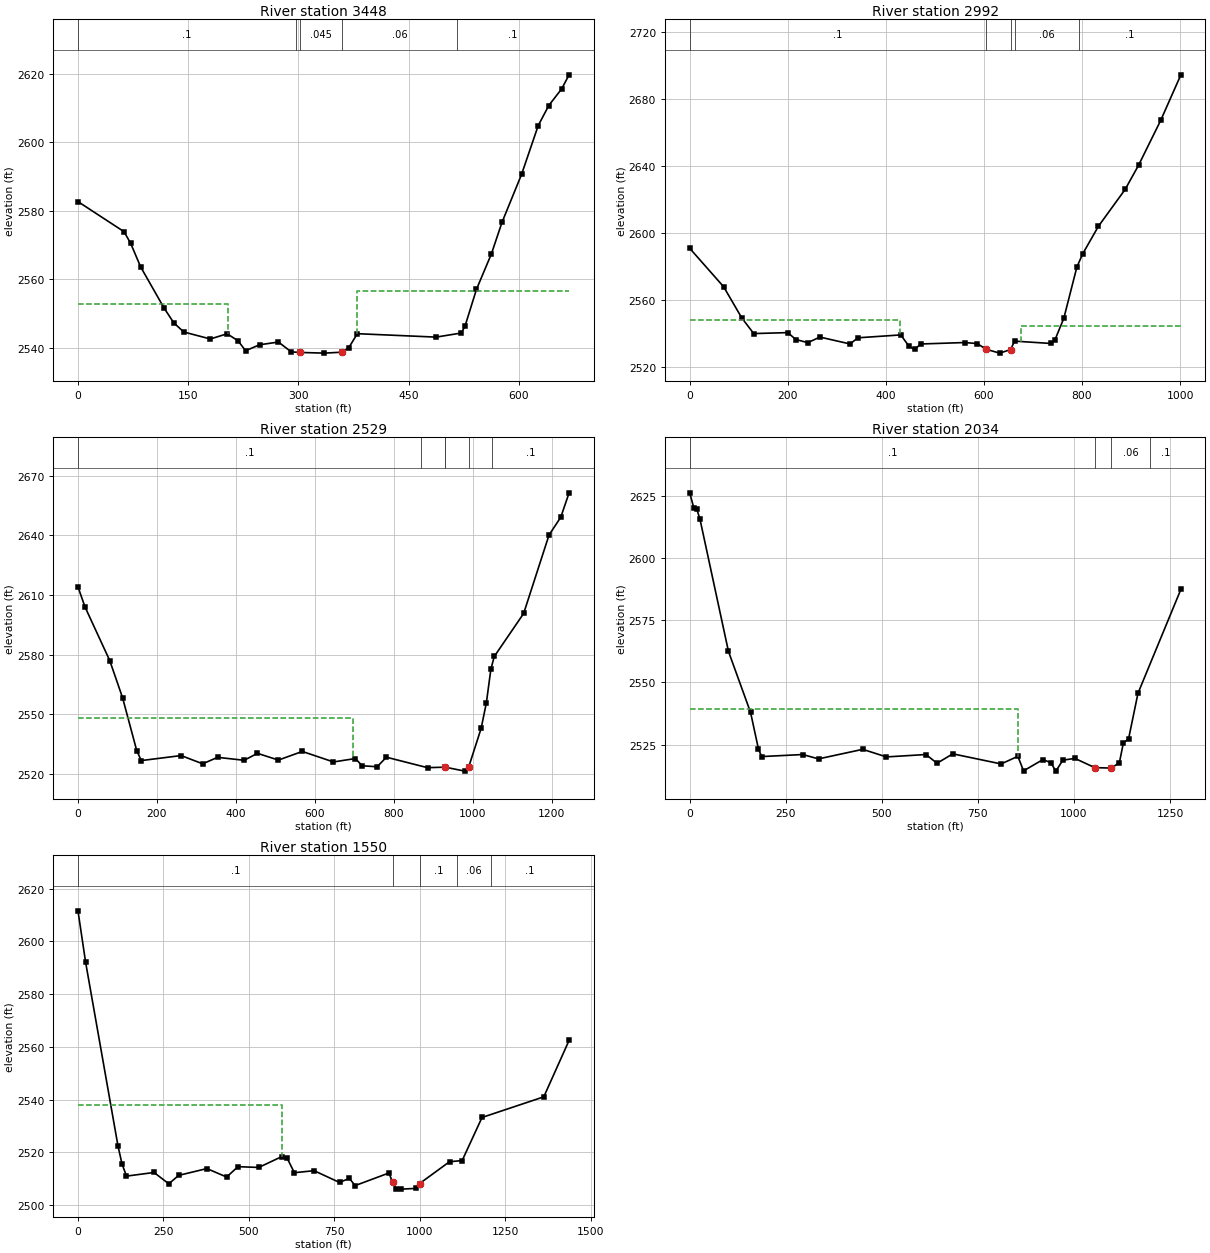
Type RM Length L Ch R = 1 ,3448    ,448.6,456.1,464.2
XS GIS Cut Line= 3
2156381.80518571485393.6319671872156482.15152186485585.202245286
2156863.46759922485827.857930878
#Sta/Elev= 30
       0 2582.72    62.7 2573.94    71.7 2570.53    85.3 2563.66   116.9 2551.76
   130.4 2547.34     144 2544.68   180.1 2542.65   202.9 2544.16   217.7 2542.14
   228.1 2539.22   247.1 2540.96   272.8 2541.75   290.1 2538.89   301.7 2538.72
   335.4 2538.52   359.7  2538.8   368.4 2540.08   380.1 2544.19   487.2 2543.19
   521.7 2544.39   526.8 2546.53   542.2 2557.13   562.5 2567.47     577 2576.71
   603.6 2590.69   626.2  2604.9   640.6 2610.75   658.1 2615.61   668.2  2619.7
#Mann= 5 ,-1,0
       0      .1       0  296.26     .06       0   301.7    .045       0
   359.7     .06       0  516.26      .1       0
#XS Ineff= 2 , 0
          204.07 2552.77  379.94         2556.78
Permanent Ineff=
       F       F
Bank Sta=301.7,359.7
XS Rating Curve= 0 ,0
Exp/Cntr(USF)=0,0
Exp/Cntr=0.3,0.1

Type RM Length L Ch R = 1 ,2992    ,459.9,462.8,468.7
XS GIS Cut Line= 3
2156092.17101315485453.4811481772156179.74599742485867.637844639
2156572.00894782486292.741414135
#Sta/Elev= 30
       0 2590.93    69.2 2567.94     106 2549.41   130.5 2540.01     200 2540.58
   216.4 2536.46   240.9  2534.6   265.4 2537.92   326.8 2533.82   343.1 2537.49
   430.4 2539.21   447.5 2532.32   458.7 2530.53   471.1 2533.79   560.6 2534.65
   586.1 2534.06     605 2530.59   632.2 2528.33   654.3 2530.43   662.5  2535.5
   736.1 2534.11   744.6 2536.03   762.9 2549.09   789.6 2579.72   801.4  2587.6
   833.6 2604.12     888  2626.1   915.3 2640.49   960.7 2667.43  1001.7 2694.57
#Mann= 5 ,-1,0
       0      .1       0     605    .045       0   654.3      .1       0
  663.31     .06       0  793.31      .1       0
#XS Ineff= 2 , 0
          428.21 2548.12  675.42         2544.81
Permanent Ineff=
       F       F
Bank Sta=605,654.3
XS Rating Curve= 0 ,0
Exp/Cntr(USF)=0,0
Exp/Cntr=0.3,0.1

Type RM Length L Ch R = 1 ,2529    ,490,495.3,499.6
XS GIS Cut Line= 3
2155601.38620545 485504.56655567  2155776.536174486046.436770864
2156176.09703975486590.131464898
#Sta/Elev= 30
       0 2614.09    17.5 2604.11    80.5 2577.03   113.1 2558.28   148.8 2531.84
   160.4 2526.79   261.3 2529.31   315.9 2525.17   353.8 2528.42     421 2526.93
   454.7 2530.43   507.8 2527.04   568.3 2531.38   647.3  2526.1   702.8 2527.82
     720 2524.18     758 2523.69   781.4 2528.49   885.6 2523.22   930.3 2523.49
   979.9 2521.49   989.9 2523.58  1021.4 2542.98  1034.7 2555.88  1046.1 2572.74
  1054.7 2579.09  1129.1  2600.7  1193.4 2640.11  1223.2 2649.06  1244.2  2661.3
#Mann= 6 ,-1,0
       0      .1       0  869.47     .08       0  929.47     .06       0
   930.3    .045       0   989.9     .06       0 1049.47      .1       0
#XS Ineff= 2 , 0
          696.77 2548.29
Permanent Ineff=
       F       F
Bank Sta=930.3,989.9
XS Rating Curve= 0 ,0
Exp/Cntr(USF)=0,0
Exp/Cntr=0.3,0.1

Type RM Length L Ch R = 1 ,2034    ,473.7,483.5,478.9
XS GIS Cut Line= 4
2155279.14392205 485607.169227942155453.13541188486338.170408876
2155639.63769321486699.0117792632155726.80723774486782.126926375
#Sta/Elev= 30
       0 2626.17    10.3 2620.22    18.5 2619.54    26.7 2615.51   100.7 2562.45
   158.3 2537.88   178.9 2523.13   187.1 2520.15     294 2520.97   335.1 2519.22
   450.2 2523.06   511.9 2520.01   614.7 2520.97   643.5 2517.47   684.6 2521.25
   810.3 2517.19   853.9 2520.25   868.7 2514.41   919.2 2518.95   939.4 2517.71
   952.9  2514.3   970.9 2518.71  1002.5 2519.41  1054.2 2515.69  1097.3 2515.53
  1118.1 2517.69  1128.5 2525.64    1142 2527.26  1166.5  2545.6  1278.1 2587.35
#Mann= 4 ,-1,0
       0      .1       0  1054.2    .045       0  1097.3     .06       0
 1197.61      .1       0
#XS Ineff= 2 , 0
          854.32 2539.12
Permanent Ineff=
       F       F
Bank Sta=1054.2,1097.3
XS Rating Curve= 0 ,0
Exp/Cntr(USF)=0,0
Exp/Cntr=0.3,0.1

Type RM Length L Ch R = 1 ,1550    ,401.8,413.9,401.6
XS GIS Cut Line= 3
2154896.95558631485755.6469238072155196.55553394486925.841122393
 2155157.1127541487151.786183557
#Sta/Elev= 30
       0 2611.63    22.2 2592.23   117.2 2522.32   128.8 2515.61     142 2510.94
   222.6 2512.32   265.8 2508.02   294.7 2511.22   377.3  2513.8   435.1 2510.59
   468.2 2514.52   529.1 2514.23   596.2 2518.33   612.1 2517.76   633.3 2512.23
   691.1    2513   765.4 2508.53   794.4  2510.1   810.9 2507.33     910 2512.12
   921.1 2508.53   930.6 2506.06   946.7    2506   990.1 2506.28   999.72508.112
  1087.5 2516.41  1124.3 2516.83  1182.5  2533.2  1363.3 2541.03  1437.3 2562.46
#Mann= 5 ,-1,0
       0      .1       0   921.1    .045       0   999.7      .1       0
    1110     .06       0 1207.94      .1       0
#XS Ineff= 2 , 0
          596.71 2537.87
Permanent Ineff=
       F       F
Bank Sta=921.1,999.7
XS Rating Curve= 0 ,0
Exp/Cntr(USF)=0,0
Exp/Cntr=0.3,0.1