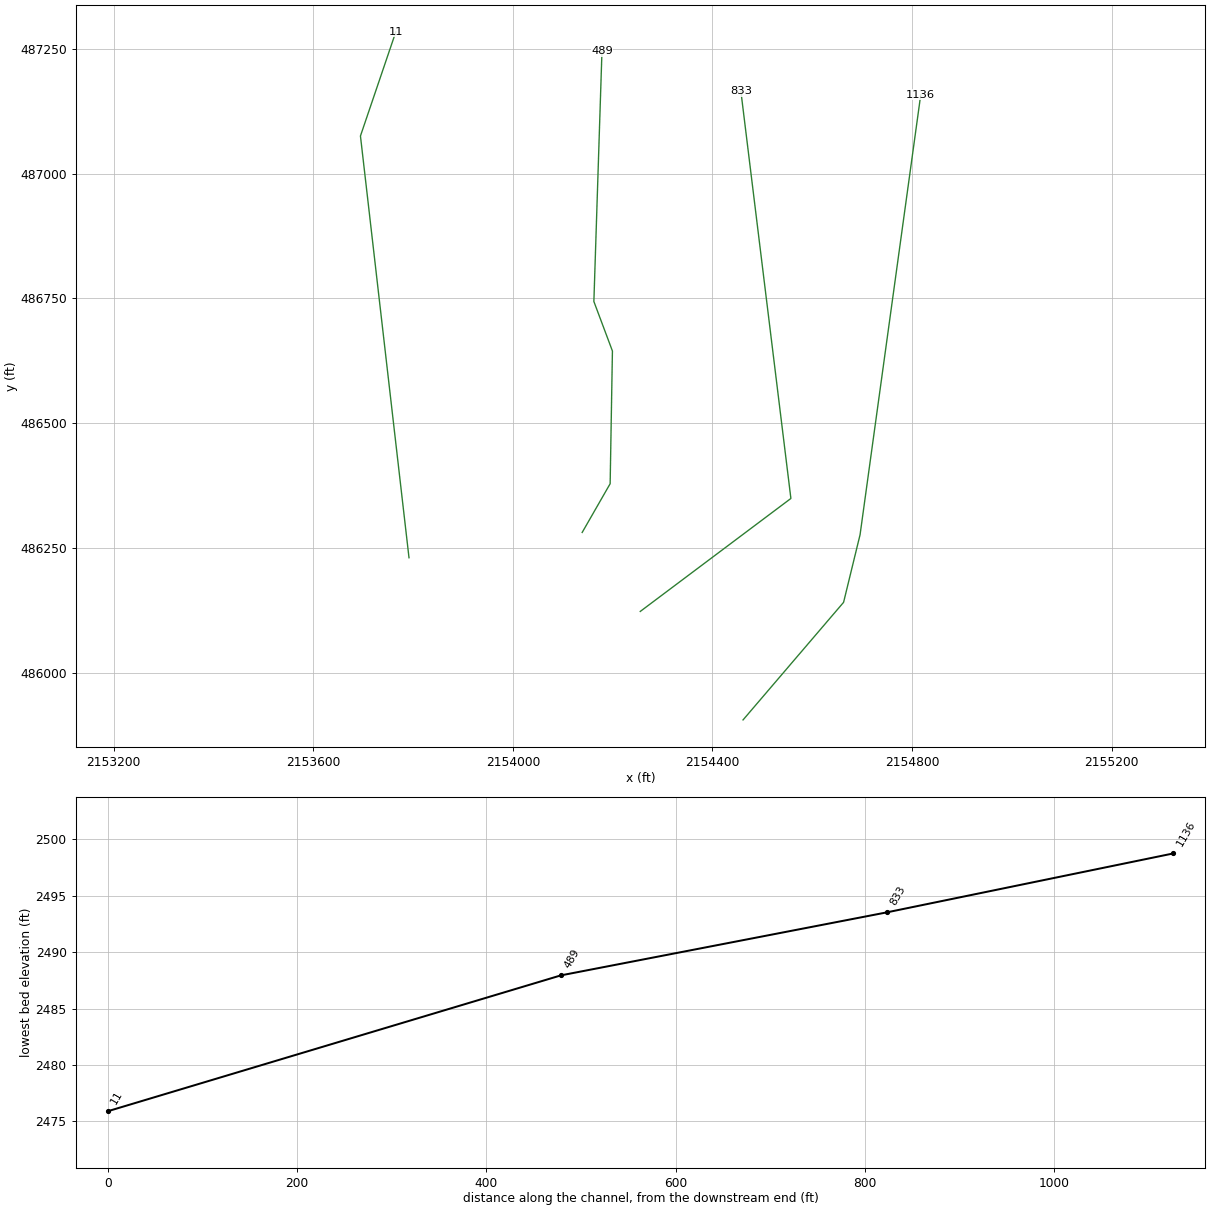
HEC-RAS study MFWILLIAMSRV.prj: MFWILLIAMSRV

--- MFWILLIAMSRV.g01 (geometry) --- (continued)

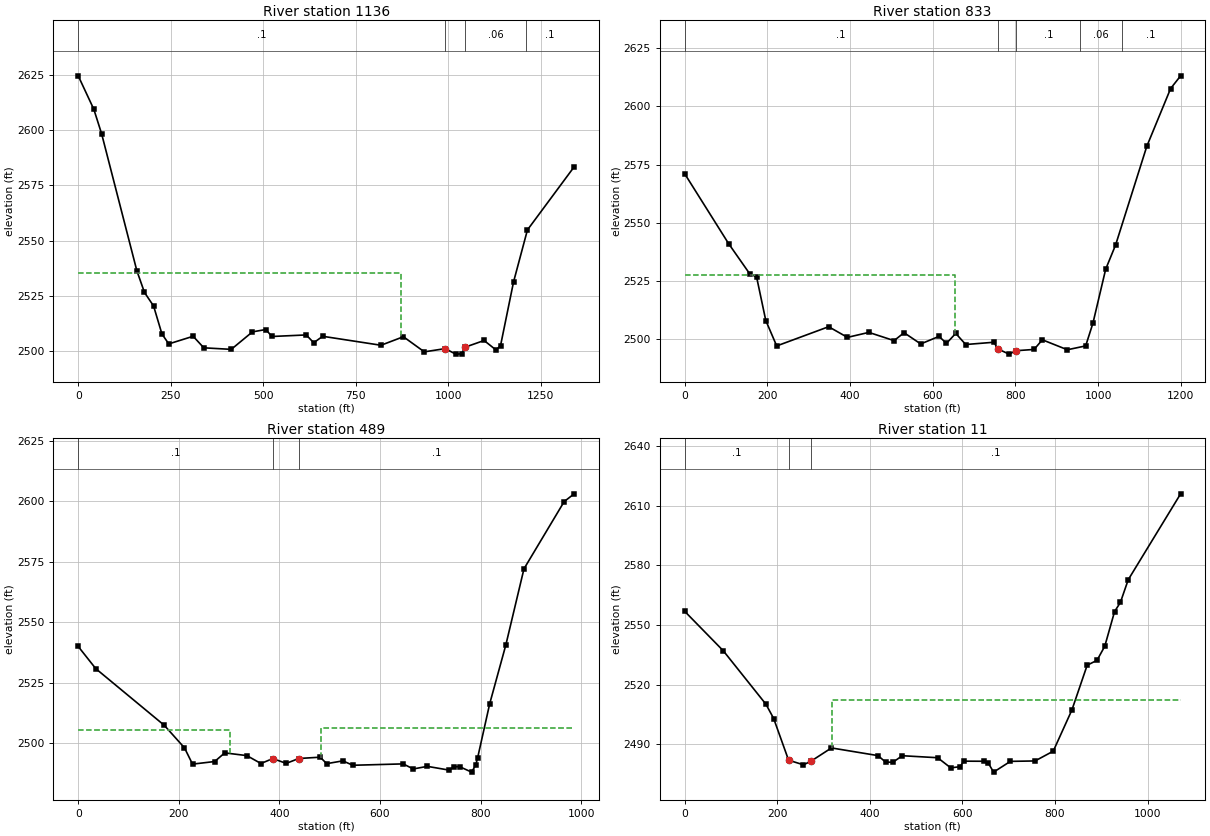
Type RM Length L Ch R = 1 ,1136    ,288.6,303.1,307.4
XS GIS Cut Line= 4
2154461.21489831485905.096665682 2154662.7350226486140.788684159
2154695.77287635486276.3388293932154817.40479895487158.170268262
#Sta/Elev= 30
       0  2624.5    42.2 2609.37    63.3 2598.28   158.4 2536.43     179 2526.61
   203.6 2520.51   226.1 2507.89   244.6 2503.37   310.5 2506.82   339.3  2501.6
   413.4  2500.9   470.7 2508.81     507 2509.87   523.1 2506.72     616 2507.42
   636.2 2503.89   660.4 2506.81   817.9 2502.76   878.5 2506.61     935 2499.78
   991.5 2501.24  1019.8 2498.75  1036.2 2498.89    1044 2501.82  1096.5 2504.91
  1128.8 2500.62  1140.9 2502.57  1176.1  2531.4  1213.6 2554.88  1339.8 2583.38
#Mann= 4 ,-1,0
       0      .1       0   991.5    .045       0    1044     .06       0
 1209.62      .1       0
#XS Ineff= 2 , 0
          871.11 2535.31
Permanent Ineff=
       F       F
Bank Sta=991.5,1044
XS Rating Curve= 0 ,0
Exp/Cntr(USF)=0,0
Exp/Cntr=0.3,0.1

Type RM Length L Ch R = 1 ,833     ,333.1,344.1,347.9
XS GIS Cut Line= 3
2154255.22663101486122.5322801652154557.11566414486348.941164144
2154456.89375745487165.110643467
#Sta/Elev= 30
       0 2571.05   106.2 2541.03   156.9 2528.15     174 2526.65   196.2 2507.97
   222.6 2497.04   348.3  2505.3   393.7 2500.72   445.5 2502.86   506.6 2499.32
   530.7 2502.73     571  2497.9   615.3 2501.15   633.3 2498.14   655.7 2502.44
   679.8 2497.65   748.4 2498.63     7572495.814   784.6 2493.52     802    2495
   845.2 2495.53   865.2 2499.68   925.7  2495.4     970 2497.05   987.6 2506.83
  1018.4    2530  1042.6 2540.53  1117.8 2582.79  1175.5 2607.67  1199.7 2613.13
#Mann= 5 ,-1,0
       0      .1       0     757    .045       0     802      .1       0
  957.36     .06       0 1057.36      .1       0
#XS Ineff= 2 , 0
          652.75 2527.42
Permanent Ineff=
       F       F
Bank Sta=757,802
XS Rating Curve= 0 ,0
Exp/Cntr(USF)=0,0
Exp/Cntr=0.3,0.1

Type RM Length L Ch R = 1 ,489     ,484.1,478.7,471.2
XS GIS Cut Line= 5
2154138.82148435486280.8358829022154194.87174239486378.487265604
2154199.43913263486644.4686738752154162.26050902486743.676370144
2154178.47848206487244.995939216
#Sta/Elev= 30
       0 2539.97    34.9 2530.79   171.3 2507.29   211.3 2497.99   227.3 2491.25
   271.3 2492.33   291.3 2495.91   335.3 2494.78   363.3 2491.51     3872493.559
   413.5 2491.56   438.6 2493.58   481.1 2494.13   494.1 2491.45   526.1  2492.6
   546.1 2490.78   646.1 2491.35   666.2 2489.25   694.2 2490.33   738.2 2488.75
   746.2 2490.13   758.2 2490.22   782.2 2487.94   790.3 2490.83   794.2 2493.88
   818.2 2516.27   850.3 2540.63   886.3 2572.11   966.3 2599.97   986.1 2603.17
#Mann= 3 ,-1,0
       0      .1       0     387    .045       0   438.6      .1       0
#XS Ineff= 2 , 0
          302.45 2505.19  481.75         2506.41
Permanent Ineff=
       F       F
Bank Sta=387,438.6
XS Rating Curve= 0 ,0
Exp/Cntr(USF)=0,0
Exp/Cntr=0.3,0.1

Type RM Length L Ch R = 1 ,11      ,,,
XS GIS Cut Line= 3
2153791.72845628486230.1275973442153694.42291819487075.469459432
2153765.37487305487284.270926567
#Sta/Elev= 30
       0 2556.86    83.6 2536.94   175.7 2510.04   192.3 2502.88   224.5 2481.91
   256.7 2479.58   273.2 2481.45   317.1 2488.08   417.8 2484.21   433.9 2480.97
   449.9 2480.87   470.1 2484.16   546.6 2483.15   574.8 2478.05     595 2478.64
     603 2481.42   647.3 2481.37   655.4 2480.68   667.4  2475.9   703.7 2481.32
     757 2481.53   796.3 2486.45   836.7 2507.24   869.6 2529.72   890.8 2532.17
   907.6 2539.26   928.8 2556.74   941.4 2561.35   958.3 2572.76  1071.5 2616.01
#Mann= 3 ,-1,0
       0      .1       0   224.5    .045       0   273.2      .1       0
#XS Ineff= 2 , 0
                          319.19         2512.14
Permanent Ineff=
       F       F
Bank Sta=224.5,273.2
XS Rating Curve= 0 ,0
Exp/Cntr(USF)=0,0
Exp/Cntr=0.3,0.1
LCMann Table=0

Chan Stop Cuts=-1
Use User Specified Reach Order=0
Composite Channel Slope=5